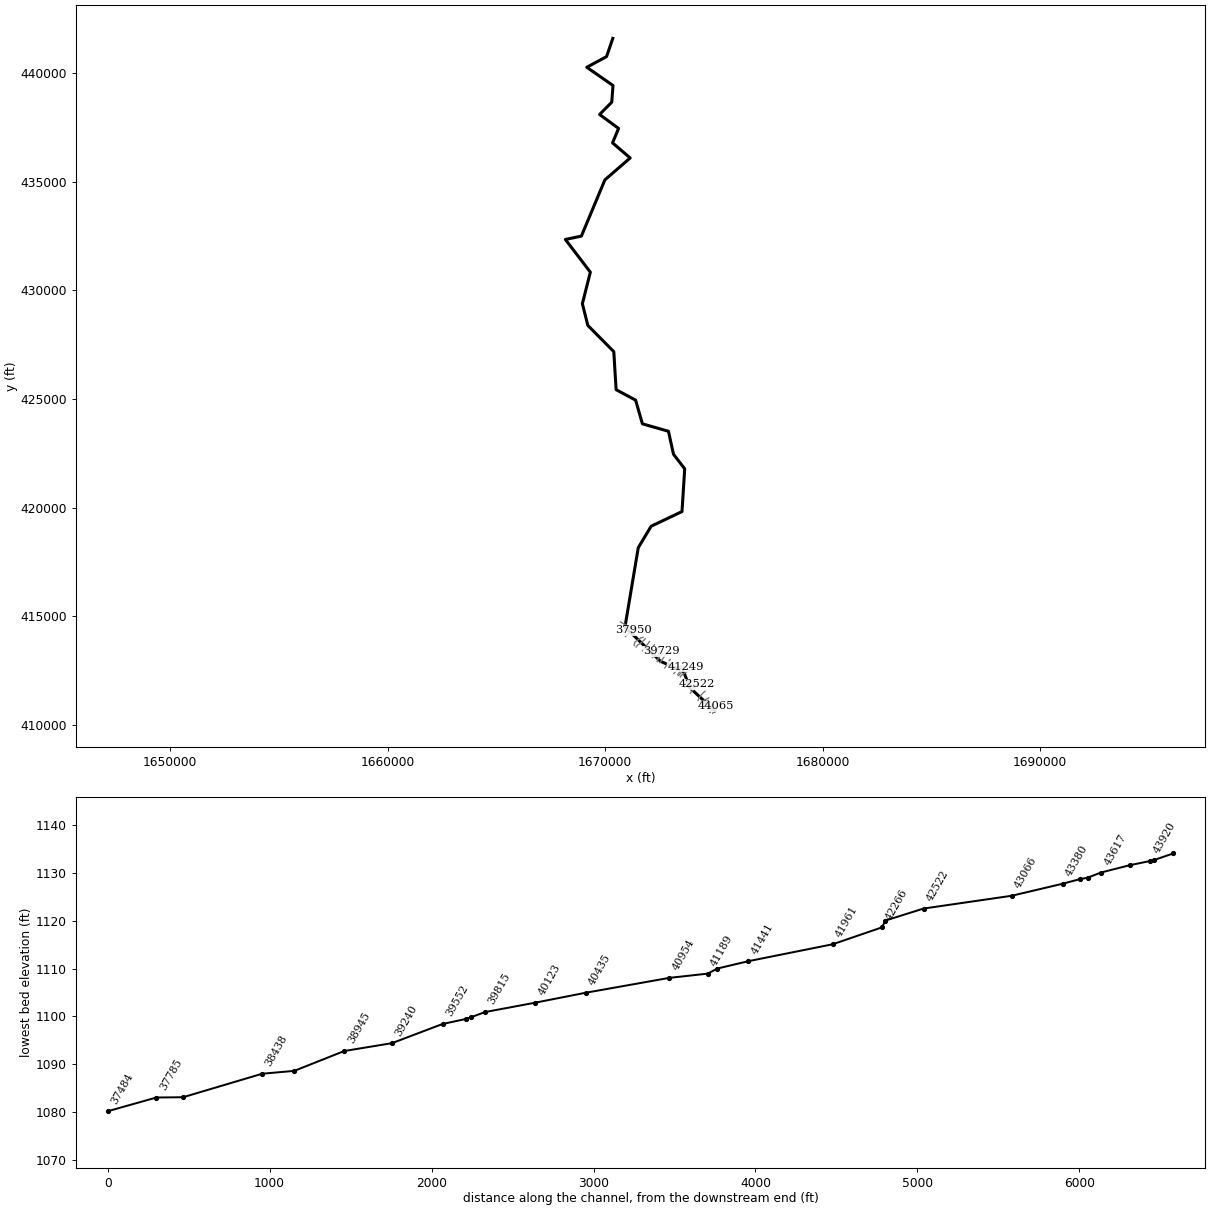
--- KNOBBFK.prj (project) ---

Proj Title=KNOBBFK
Current Plan=p01
Default Exp/Contr=0,0
English Units
Geom File=g01
Flow File=f01
Plan File=p01
BEGIN DESCRIPTION:
---------- MODELED AS PART OF WVEMD CTP PROGRAM, 2023----------
Stream Name: Knobb Fork
Flood Zone:  AFH
Wetzel County, WV
HEC-RAS Version: RAS 6.3
Vertical Datum: NAVD88
Projection: NAD 1983 StatePlane West Virginia S FIPS 4702 (US Feet)
Terrain: 1-meter West Virginia FEMA R3 South Central (collected 2018-2020)
Land Use: 2019 NLCD
Hydrologic Method:
WV SIR2010-5033 regression equations
Additional Model Notes:
None
END DESCRIPTION:
DSS Export Rating Curves= 0
DSS Export Rating Curve Sorted= 0
DSS Export Volume Flow Curves= 0
DXF OffsetX= 0
DXF OffsetY= 0
DXF ScaleX= 0
DXF ScaleY= 0

--- KNOBBFK.p01 (plan) ---

Plan Title=Floodplain
Program Version=6.30
Short Identifier=Floodplain
Geom File=g01
Flow File=f01
Subcritical Flow
K Sum by GR= 0
Std Step Tol= 0.01
Critical Tol= 0.01
Num of Std Step Trials= 20
Max Error Tol= 0.3
Flow Tol Ratio= 0.001
Split Flow NTrial= 30
Split Flow Tol= 0.02
Split Flow Ratio= 0.02
Log Output Level= 0
Friction Slope Method= 1
Unsteady Friction Slope Method= 2
Unsteady Bridges Friction Slope Method= 1
Parabolic Critical Depth
Global Vel Dist= 0 , 0 , 0
Global Log Level= 0
CheckData=True
Encroach Param=-1 ,0,0, 0
Mapping Interval=1HOUR
Computation Time Step Use Courant=        0
Computation Time Step Use Time Series=    0
Computation Time Step Count To Double=0
Computation Time Step Max Doubling=0
Computation Time Step Max Halving=0
Computation Time Step Residence Courant=0
Run HTab= 0
Run UNet= 0
Run Sediment= 0
Run PostProcess= 0
Run WQNet= 0
Run RASMapper= 0
UNET Theta= 0
UNET Theta Warmup= 0
UNET ZTol= 0
UNET ZSATol= 0
UNET MxIter= 0
UNET Max Iter WO Improvement= 0
UNET MaxInSteps= 0
UNET DtIC= 0
UNET DtMin= 0
UNET MaxCRTS= 0
UNET WFStab= 0
UNET SFStab= 0
UNET WFX= 1
UNET SFX= 1
UNET Gravity=32.17405
UNET 1D Methodology=Finite Difference
UNET DSS MLevel= 1
UNET Pardiso=0
UNET DZMax Abort= 0
UNET Use Existing IB Tables= 0
UNET Froude Reduction=False
UNET Froude Limit= 0
UNET Froude Power= 0
UNET D1 Cores= 0
UNET WindReference=Eulerian
UNET WindDragFormulation=Hsu (1988)
UNET D2 Coriolis=0
UNET D2 Cores= 0
UNET D2 Theta= 1
UNET D2 Theta Warmup= 1
UNET D2 Z Tol= 0.01
UNET D2 Volume Tol= 0.01
UNET D2 Max Iterations= 20
UNET D2 Equation= 0
UNET D2 RampUpFraction=0.1
UNET D2 TimeSlices= 1
UNET D2 Turbulence Formulation=Non-Conservative (original)
UNET D2 Eddy Viscosity=0.3
UNET D2 Transverse Eddy Viscosity=0.1
UNET D2 Smagorinsky Mixing=0
UNET D2 BCVolumeCheck=0
UNET D2 Cores=0
UNET D2 SolverType=PARDISO (Direct)
UNET D2 Minimum Iterations= 3
UNET D2 Maximum Iterations= 30
UNET D2 Restart Number= 10
UNET D2 Relaxation Coeff=1.3
UNET D2 SOR Precondition Iterations= 10
UNET D2 ILUT Maximum Fill= 8
UNET D2 ILUT Tolerance=1E-08
UNET D2 Convergence Tolerance=0.00001
UNET D1D2 MaxIter= 0
UNET D1D2 ZTol=0.01
UNET D1D2 QTol=0.1
UNET D1D2 MinQTol=1
Write IC File= 0
Write IC File at Fixed DateTime=0
Write IC File at Sim End=0
Echo Input=False
Echo Parameters=False
Echo Output=False
Write Detailed= 0
HDF Write Warmup=0
HDF Write Time Slices=0
HDF Flush=0
HDF Compression= 1
HDF Chunk Size= 1
HDF Spatial Parts= 1
HDF Use Max Rows=0
HDF Fixed Rows= 1
Calibration Method= 0
Calibration Iterations= 20
Calibration Max Change=0.05
Calibration Tolerance=0.2
Calibration Maximum=1.5
Calibration Minimum=0.5
Calibration Optimization Method= 1
WQ AD Non Conservative
WQ ULTIMATE=-1
WQ Max Comp Step=1HOUR
WQ Output Interval=15MIN
WQ Output Selected Increments= 0
WQ Output face flow=0
WQ Output face velocity=0
WQ Output face area=0
WQ Output face dispersion=0
WQ Output cell volume=0
WQ Output cell surface area=0
WQ Output cell continuity=0
WQ Output cumulative cell continuity=0
WQ Output face conc=0
WQ Output face dconc_dx=0
WQ Output face courant=0
WQ Output face peclet=0
WQ Output face adv mass=0
WQ Output face disp mass=0
WQ Output cell mass=0
WQ Output cell source sink temp=0
WQ Output nsm pathways=0
WQ Output nsm derived pathways=0
WQ Create Restart=0
WQ Fixed Restart=0
WQ System Summary=0
WQ Write To DSS=0
Sorting and Armoring Iterations= 10
XS Update Threshold= 0.02
Bed Roughness Predictor= 0
Hydraulics Update Threshold= 0.02
Energy Slope Method= 1
Volume Change Method= 1
Sediment Retention Method= 0
Sediment TS Multiplier= 1
Warm Up Method= 0
XS Weighting Method= 0
Number of US Weighted Cross Sections= 1
Number of DS Weighted Cross Sections= 1
Upstream XS Weight=0
Main XS Weight=1
Downstream XS Weight=0
Number of DS XS's Weighted with US Boundary= 1
Upstream Boundary Weight= 1
Weight of XSs Associated with US Boundary= 0
Number of US XS's Weighted with DS Boundary= 1
Downstream Boundary Weight= 0.5
Weight of XSs Associated with DS Boundary= 0.5
Percentile Method= 0
Sediment Output Level= 3
Mass or Volume Output= 0
Output Increment Type= 1
Profile and TS Output Increment= 1
Transport Output Increment 1
XS Output Flag= 0
XS Output Increment= 10
Read HDF5 Sediment Hotstart= 0
Sediment Hotstart Type= 0
Write Gradation File= 0
Read Gradation Hotstart= 0
Write HDF5 File= 1
Write Binary Output= 1
Write DSS Sediment File= 0
DSS Sediment Output Type= 1
SV Curve= 0
Specific Gage Flag= 0
Subcell Erosion Methods= 0
Subcell Deposition Methods= 0
Advection Scheme= 1
Matrix Solver= 0
Implicit Weighting Factor= 1
Maximum Outer Loop Convergence Iterations= 5
Convergence Maximum Absolute= 0.001
Convergence RMSE= 0.0001
Grain Fractions Max Abs Error= 0.001
Max Subgrid Regions= 1
Max Subgrid Length Scale= 3.402823E+38
Initial Layer Thickness= 3.402823E+38
Min Layer Thickness= 3.402823E+38
Max Layer Thickness= 3.402823E+38
Number of Layers= 5

--- KNOBBFK.f01 (steady flow) ---

Flow Title=Flow
Program Version=6.30
Number of Profiles= 1
Profile Names=F01pct
River Rch & RM=KNOBBFK,Main,44065
     588
River Rch & RM=KNOBBFK,Main,43380
     656
River Rch & RM=KNOBBFK,Main,40954
     743
River Rch & RM=KNOBBFK,Main,40435
     826
River Rch & RM=KNOBBFK,Main,37950
     933
River Rch & RM=KNOBBFK,Main,37484
    1080
River Rch & RM=KNOBBFK,Main,36093
    1220
River Rch & RM=KNOBBFK,Main,31113
    1450
River Rch & RM=KNOBBFK,Main,28472
    1640
River Rch & RM=KNOBBFK,Main,25433
    2110
River Rch & RM=KNOBBFK,Main,18483
    2570
River Rch & RM=KNOBBFK,Main,11439
    2880
Boundary for River Rch & Prof#=KNOBBFK,Main            , 1
Up Type= 0
Dn Type= 3
Dn Slope=0.00758
DSS Import GetInterval= 0
DSS Import GetPeak= 0
DSS Import FillOption= 0

--- KNOBBFK.g01 (geometry) ---

Geom Title=Geometry
Program Version=6.30

River Reach=KNOBBFK         ,Main
Reach XY= 30
1675034.85699999410661.5429999981673886.93595995411726.589128524
     1673602.191412464.878000006     1672539.839412938.784999996
1670905.20700002      414515.5221671516.38700001418163.455000013
1672108.23568818419150.4768709691673528.02600001419824.634000018
1673652.39200002421790.4210000041673135.80400001422461.400999993
     1672904.508423517.2900000211671707.39700001423858.677000001
1671395.18300001424947.433000013     1670497.913425429.039000005
1670391.51199999427178.0820000021669197.87400001 428384.22300002
1668946.78300001 429381.642000021669313.17399999430833.317000002
1668163.98899999432337.4329999981668900.37600002432489.893999994
1669981.69700001435076.6990000011671144.45299999436084.487000003
     1670334.735436778.7680000071670611.08499999437443.728000015
     1669737.419 438083.343000011670298.04900001438649.856000021
1670354.92900002439417.4180000131669149.63600001440254.877000004
1670057.84209384440744.5590572061670346.72369337441585.463758796

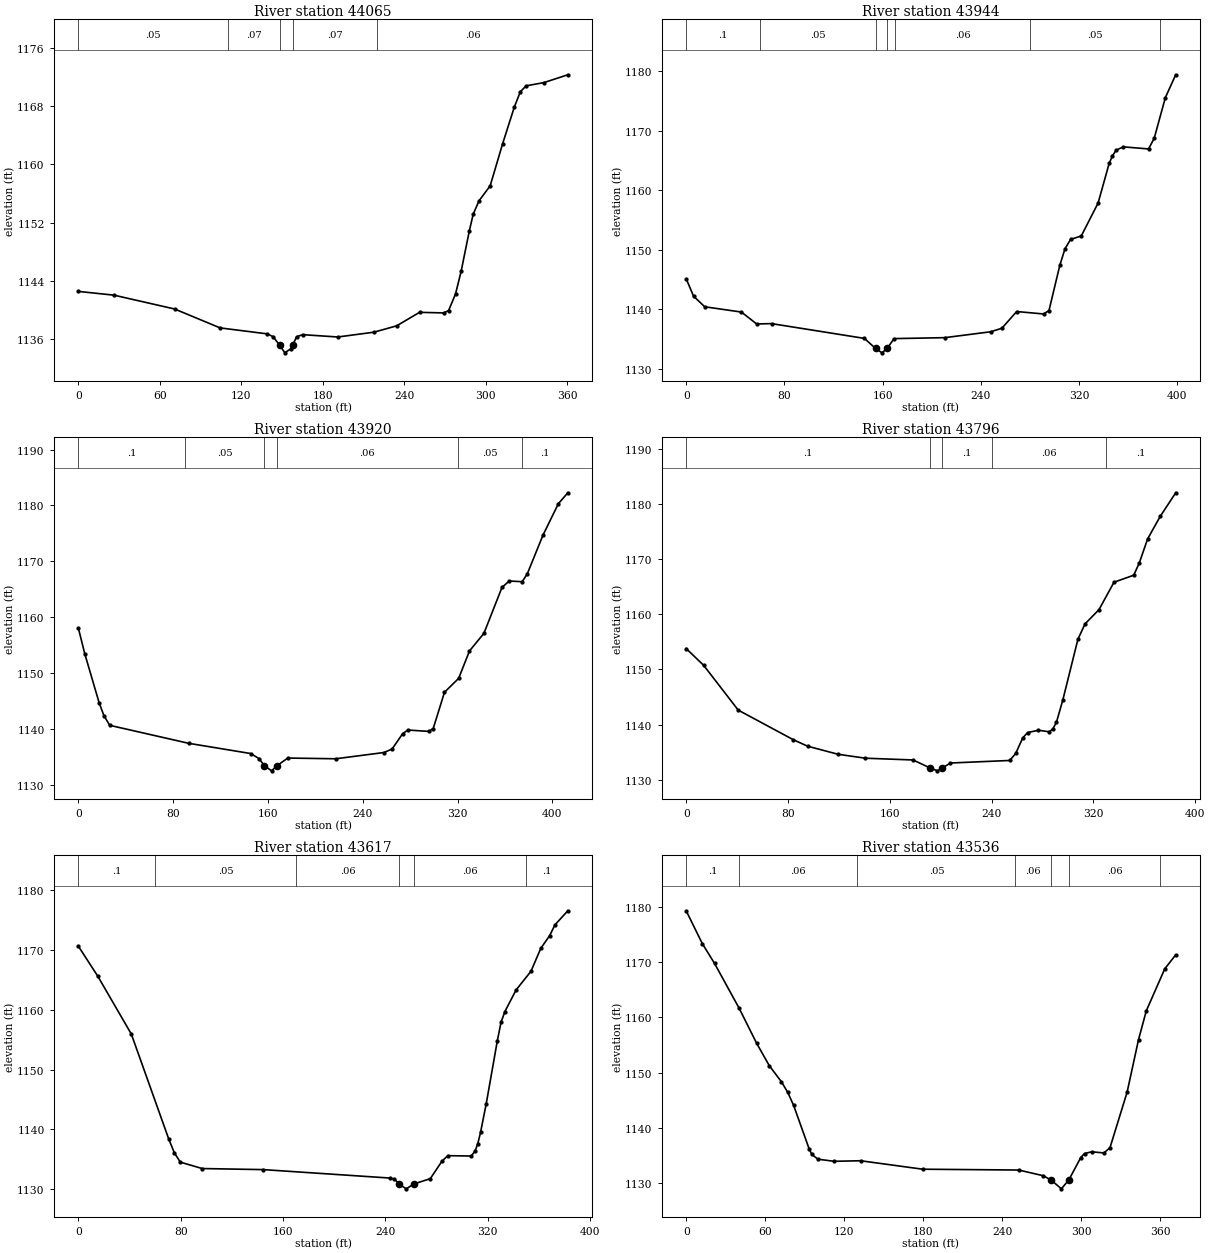
Type RM Length L Ch R = 1 ,44065   ,121.1,121.3,120.7
XS GIS Cut Line= 2
1674939.58325173410544.251992522  1675078.676633410876.866599892
#Sta/Elev= 30
       0 1142.53    26.3 1142.01    70.9 1140.11   104.4 1137.51   139.1 1136.69
   143.4 1136.31  148.43 1135.09   152.1 1134.08   156.4 1134.63  157.79 1135.09
   160.7 1136.28   165.1 1136.58   191.1 1136.26   217.7 1136.92   234.4 1137.79
   251.3 1139.65   269.1 1139.57   272.7  1139.9   277.8 1142.18   281.9 1145.28
     288 1150.89   290.8 1153.14   295.1 1154.99   303.3 1157.05   312.5 1162.85
   321.1 1167.88   325.5 1169.98   329.8  1170.8   342.8 1171.24   360.5 1172.32
#Mann= 5 ,-1,0
       0     .05       0     110     .07       0  148.43    .045       0
  157.79     .07       0     220     .06       0
Bank Sta=148.43,157.79
XS Rating Curve= 0 ,0
Exp/Cntr(USF)=0,0
Exp/Cntr=0.3,0.1

Type RM Length L Ch R = 1 ,43944   ,24.5,24.4,24.3
XS GIS Cut Line= 3
1674825.66255673410591.0553941831674959.54918815410888.518997876
1674994.84148012410951.821045366
#Sta/Elev= 30
       0 1145.13       6  1142.2    15.1 1140.42      45 1139.53    57.4 1137.53
    69.5 1137.59   145.1 1135.11   154.2 1133.43   159.5 1132.68   163.9 1133.48
   169.3 1135.07   210.6 1135.23     248 1136.22   257.1 1136.81   269.2 1139.62
   291.1 1139.21   295.5 1139.79   304.3 1147.37   308.5 1150.15   313.1 1151.74
   321.8 1152.32   335.5 1157.85   344.5  1164.5   347.2 1165.78   350.2 1166.73
     356 1167.29   376.6 1166.94   381.2 1168.73   390.3 1175.57   398.7  1179.4
#Mann= 7 ,-1,0
       0      .1       0      60     .05       0   154.2    .045       0
   163.9     .05       0     170     .06       0     280     .05       0
  386.21      .1       0
Bank Sta=154.2,163.9
XS Rating Curve= 0 ,0
Exp/Cntr(USF)=0,0
Exp/Cntr=0.3,0.1

Type RM Length L Ch R = 1 ,43920   ,123.8,123.2,120.1
XS GIS Cut Line= 3
1674800.43397141410600.9728220741674938.86757414410894.752788287
1674973.90521203 410975.82022802
#Sta/Elev= 30
       0 1158.07     5.4 1153.47    17.5 1144.71    21.6 1142.36    26.5 1140.63
    93.1 1137.41   145.4 1135.58   152.7 1134.65   156.81133.435   163.1 1132.48
   167.5 1133.38   176.8 1134.77   217.2 1134.64   257.9 1135.76   264.8 1136.39
   273.7 1139.13   278.1 1139.79   295.8 1139.54   299.5 1140.06     309 1146.55
     321 1149.05   330.1 1153.95   342.3 1157.11   357.5 1165.31   363.6 1166.47
   374.6 1166.35     379 1167.81   392.1 1174.67   405.1 1180.31   413.1 1182.27
#Mann= 6 ,-1,0
       0      .1       0      90     .05       0   156.8    .045       0
   167.5     .06       0     320     .05       0  374.76      .1       0
Bank Sta=156.8,167.5
XS Rating Curve= 0 ,0
Exp/Cntr(USF)=0,0
Exp/Cntr=0.3,0.1

Type RM Length L Ch R = 1 ,43796   ,178.9,179,176.3
XS GIS Cut Line= 2
 1674674.9656197410702.5208410831674936.35366469410984.739295821
#Sta/Elev= 30
       0 1153.79    13.7 1150.76    40.9 1142.63    84.3 1137.25    95.4 1136.09
   119.4 1134.62   140.9 1133.91   178.3 1133.59   191.9 1132.12   197.5 1131.62
  201.25 1132.13   207.7 1133.04   254.2  1133.5     259 1134.78   264.4 1137.56
   268.3 1138.56   276.8 1138.98   285.3  1138.7   288.1  1139.2     291 1140.44
     296 1144.47   307.9 1155.51   313.5 1158.28   324.4 1160.84   336.2 1165.82
   351.7 1167.09   356.1 1169.31   362.6 1173.66   372.5 1177.74   384.7 1182.04
#Mann= 5 ,-1,0
       0      .1       0   191.9    .045       0  201.25      .1       0
     240     .06       0     330      .1       0
Bank Sta=191.9,201.25
XS Rating Curve= 0 ,0
Exp/Cntr(USF)=0,0
Exp/Cntr=0.3,0.1

Type RM Length L Ch R = 1 ,43617   ,80.9,81,80.8
XS GIS Cut Line= 2
1674495.55531633410860.428785996 1674824.8101802411055.293909506
#Sta/Elev= 30
       0 1170.61    15.1 1165.63    41.4 1155.94    70.6 1138.44      75 1136.12
    79.7 1134.54    96.8 1133.47   144.7 1133.29   243.7 1131.88     247 1131.72
  250.921130.857   256.3 1130.08  262.291130.895   275.1 1131.78   284.2 1134.69
   288.8 1135.62   307.1 1135.56     310 1136.38   312.1 1137.52   314.4 1139.53
   318.8 1144.27   327.5 1154.81   330.4 1157.91   333.4 1159.68   342.1 1163.28
   353.8 1166.42   361.5 1170.26   368.4 1172.37   372.5 1174.16   382.6 1176.52
#Mann= 6 ,-1,0
       0      .1       0      60     .05       0     170     .06       0
  250.92    .045       0  262.29     .06       0     350      .1       0
Bank Sta=250.92,262.29
XS Rating Curve= 0 ,0
Exp/Cntr(USF)=0,0
Exp/Cntr=0.3,0.1

Type RM Length L Ch R = 1 ,43536   ,50.5,50,49.8
XS GIS Cut Line= 2
1674429.51297883410917.7719722341674751.30060854411103.860981986
#Sta/Elev= 30
       0 1179.29    12.2 1173.37    21.5 1169.78      40 1161.76    53.5 1155.33
    63.1 1151.28    72.3 1148.38    77.1 1146.46    81.6 1144.09    93.4 1136.21
    95.4 1135.24     100 1134.37   112.3 1133.99   132.4 1134.09   179.6 1132.56
   252.5 1132.41     271 1131.39   277.2 1130.59   284.9 1129.01  290.641130.656
   299.6 1134.66   302.5  1135.4     308 1135.71   317.2  1135.5   321.8 1136.45
   334.8 1146.48   343.5 1156.01   349.4 1161.21   363.4 1168.79   371.7 1171.32
#Mann= 7 ,-1,0
       0      .1       0      40     .06       0     130     .05       0
     250     .06       0   277.2    .045       0  290.64     .06       0
     360      .1       0
Bank Sta=277.2,290.64
XS Rating Curve= 0 ,0
Exp/Cntr(USF)=0,0
Exp/Cntr=0.3,0.1

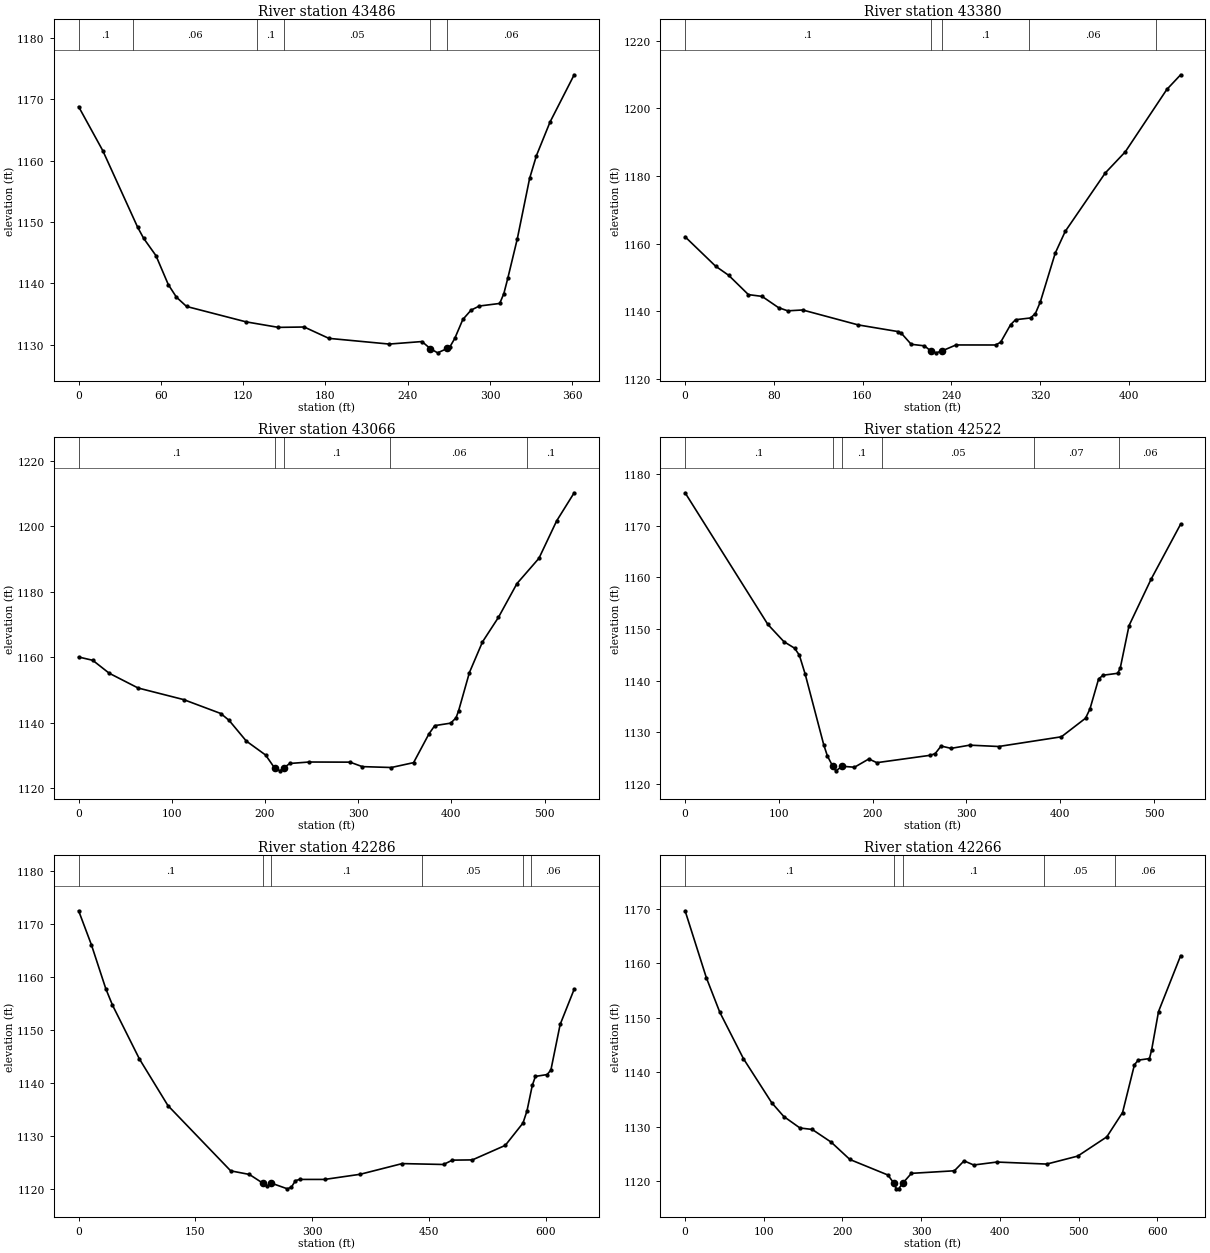
Type RM Length L Ch R = 1 ,43486   ,104.3,106.1,105.1
XS GIS Cut Line= 3
1674405.63858924 410979.398472931674673.14993263411112.160168808
1674729.16944368411140.515723786
#Sta/Elev= 30
       0 1168.81    17.6 1161.65      43 1149.18    47.4 1147.36    56.4 1144.53
    65.4 1139.81    71.3 1137.77    78.7 1136.25   122.1 1133.74   145.7 1132.84
   164.5  1132.9   182.5 1131.05   226.5 1130.12   250.4 1130.53   256.4 1129.39
   261.8 1128.69268.88671129.408   270.7 1129.64   274.3 1131.03   280.2 1134.13
   286.2 1135.65   292.2 1136.32   307.1 1136.74   310.1 1138.34     313 1140.85
   319.9 1147.25   328.9 1157.12   333.9 1160.85   343.8 1166.31   361.4 1174.01
#Mann= 6 ,-1,0
       0      .1       0      40     .06       0     130      .1       0
     150     .05       0   256.4    .045       0268.8867     .06       0
Bank Sta=256.4,268.8867
XS Rating Curve= 0 ,0
Exp/Cntr(USF)=0,0
Exp/Cntr=0.3,0.1

Type RM Length L Ch R = 1 ,43380   ,309.9,314.1,312.9
XS GIS Cut Line= 4
 1674360.7620207 411059.202366841674514.08218519411133.599734767
1674669.69193812411211.7504106811674760.29139427411259.470734911
#Sta/Elev= 30
       0 1162.04    27.5 1153.35    39.3 1150.65    57.1 1144.94    69.4 1144.42
    84.3 1141.08    92.6 1140.15     106  1140.4   156.2 1135.98     192 1134.02
   195.1 1133.49   203.9 1130.26   215.8  1129.8221.52361128.304   226.4 1127.73
231.82361128.314   244.3 1130.06   280.1 1130.05   284.6 1130.88   293.5 1136.03
     298 1137.52   311.5 1138.04   315.9 1139.34   320.4 1142.82   333.8  1157.2
   342.8 1163.62   378.9 1180.89     397 1187.16   434.4 1205.58   446.9 1209.93
#Mann= 5 ,-1,0
       0      .1       0221.5236    .045       0231.8236      .1       0
  310.42     .06       0  424.55      .1       0
Bank Sta=221.5236,231.8236
XS Rating Curve= 0 ,0
Exp/Cntr(USF)=0,0
Exp/Cntr=0.3,0.1

Type RM Length L Ch R = 1 ,43066   ,541.1,544,537.9
XS GIS Cut Line= 4
1674264.67760444411142.9482422671674339.89361756411300.367664968
1674484.30613022411475.3492496571674585.50029968411557.569512342
#Sta/Elev= 30
       0 1160.04    15.1 1159.04    32.8 1155.08    63.8 1150.56   112.6 1147.02
   152.5 1142.76   161.4 1140.67   179.9 1134.33   200.6 1130.06210.16121126.136
   216.2 1125.22220.16121126.119   226.5 1127.47   247.3 1127.92   291.2 1127.88
   304.3 1126.51   335.5 1126.24   359.4 1127.73   375.9 1136.53   382.1 1139.05
   399.2 1139.81   404.9 1141.42   407.7 1143.59   419.3 1155.29   433.3 1164.65
   450.4 1172.15   470.3  1182.5   493.9 1190.24   512.9 1201.68   531.7 1210.28
#Mann= 5 ,-1,0
       0      .1       0210.1612    .045       0220.1612      .1       0
  334.47     .06       0  481.34      .1       0
Bank Sta=210.1612,220.1612
XS Rating Curve= 0 ,0
Exp/Cntr(USF)=0,0
Exp/Cntr=0.3,0.1

Type RM Length L Ch R = 1 ,42522   ,241.2,236.4,228.2
XS GIS Cut Line= 4
1673910.19027723411471.5917491171673960.79892966411545.335785502
1674114.07084842411692.8238582721674228.30180674411888.028660468
#Sta/Elev= 30
       0 1176.36    88.2 1150.89   105.4 1147.54   116.7 1146.29   121.8 1144.94
     128 1141.28   147.8  1127.6   151.7 1125.43   157.5 1123.41   160.7 1122.55
   167.6 1123.43   180.6 1123.25   195.9 1124.85   204.4 1124.13   261.4 1125.56
   266.6 1125.88   272.9 1127.35   283.6  1126.9   303.4 1127.52   334.3 1127.26
   401.2 1129.14   426.9 1132.73   431.6 1134.51   440.8 1140.31   445.5 1141.05
   461.3 1141.43     464 1142.51   473.3 1150.66   496.7  1159.6   528.3 1170.29
#Mann= 6 ,-1,0
       0      .1       0   157.5    .045       0   167.6      .1       0
  209.44     .05       0  372.15     .07       0  462.15     .06       0
Bank Sta=157.5,167.6
XS Rating Curve= 0 ,0
Exp/Cntr(USF)=0,0
Exp/Cntr=0.3,0.1

Type RM Length L Ch R = 1 ,42286   ,18.7,19.2,18.7
XS GIS Cut Line= 6
1673675.82407702411739.2676628021673832.93913332411803.505610148
1673881.18308665411780.2160369931673977.37979103411696.724557719
1674007.78157968411693.5482514421674197.13038086411864.644183513
#Sta/Elev= 30
       0 1172.56    16.5  1166.1    34.9 1157.83    43.5 1154.73    78.1 1144.56
   114.7 1135.76   195.3 1123.43   219.3 1122.75   236.5 1121.11   241.9 1120.52
  246.89 1121.14   268.2 1120.03   273.4 1120.38   278.5 1121.57   283.7 1121.81
   316.1 1121.81   361.6 1122.78   415.6  1124.8   468.7 1124.63     480 1125.45
   505.8  1125.5     548 1128.24   570.8 1132.47   575.9 1134.76   582.7 1139.57
   586.7 1141.27   601.8 1141.62   606.6 1142.48   618.5 1151.09   636.5 1157.74
#Mann= 6 ,-1,0
       0      .1       0   236.5    .045       0  246.89      .1       0
  441.35     .05       0  571.35     .07       0  581.35     .06       0
Bank Sta=236.5,246.89
XS Rating Curve= 0 ,0
Exp/Cntr(USF)=0,0
Exp/Cntr=0.3,0.1

Type RM Length L Ch R = 1 ,42266   ,293.7,305.6,309.7
XS GIS Cut Line= 6
1673662.82687896411765.5763811351673822.56277616 411826.04917721
1673890.10648098411795.7932648021673926.55889061411765.695779728
1673982.67235039411716.5366036761674190.50103471411877.788782529
#Sta/Elev= 30
       0  1169.6      27 1157.33    44.1    1151    74.1  1142.5     110 1134.43
   125.4 1131.89     146 1129.78   161.5 1129.52   185.6 1127.19   209.4 1124.01
   257.8 1121.16   265.3 1119.65   268.2 1118.69   271.3 1118.63  276.831119.705
   287.6 1121.47   342.2 1121.94   354.5 1123.76   366.7    1123   396.2 1123.54
   459.6 1123.17   498.9 1124.63   535.9 1128.16   555.9 1132.62     571 1141.38
   575.8 1142.22   590.1 1142.51   592.9 1144.13   601.6 1151.13   629.7 1161.37
#Mann= 5 ,-1,0
       0      .1       0   265.3    .045       0  276.83      .1       0
  456.68     .05       0  546.68     .06       0
Bank Sta=265.3,276.83
XS Rating Curve= 0 ,0
Exp/Cntr(USF)=0,0
Exp/Cntr=0.3,0.1

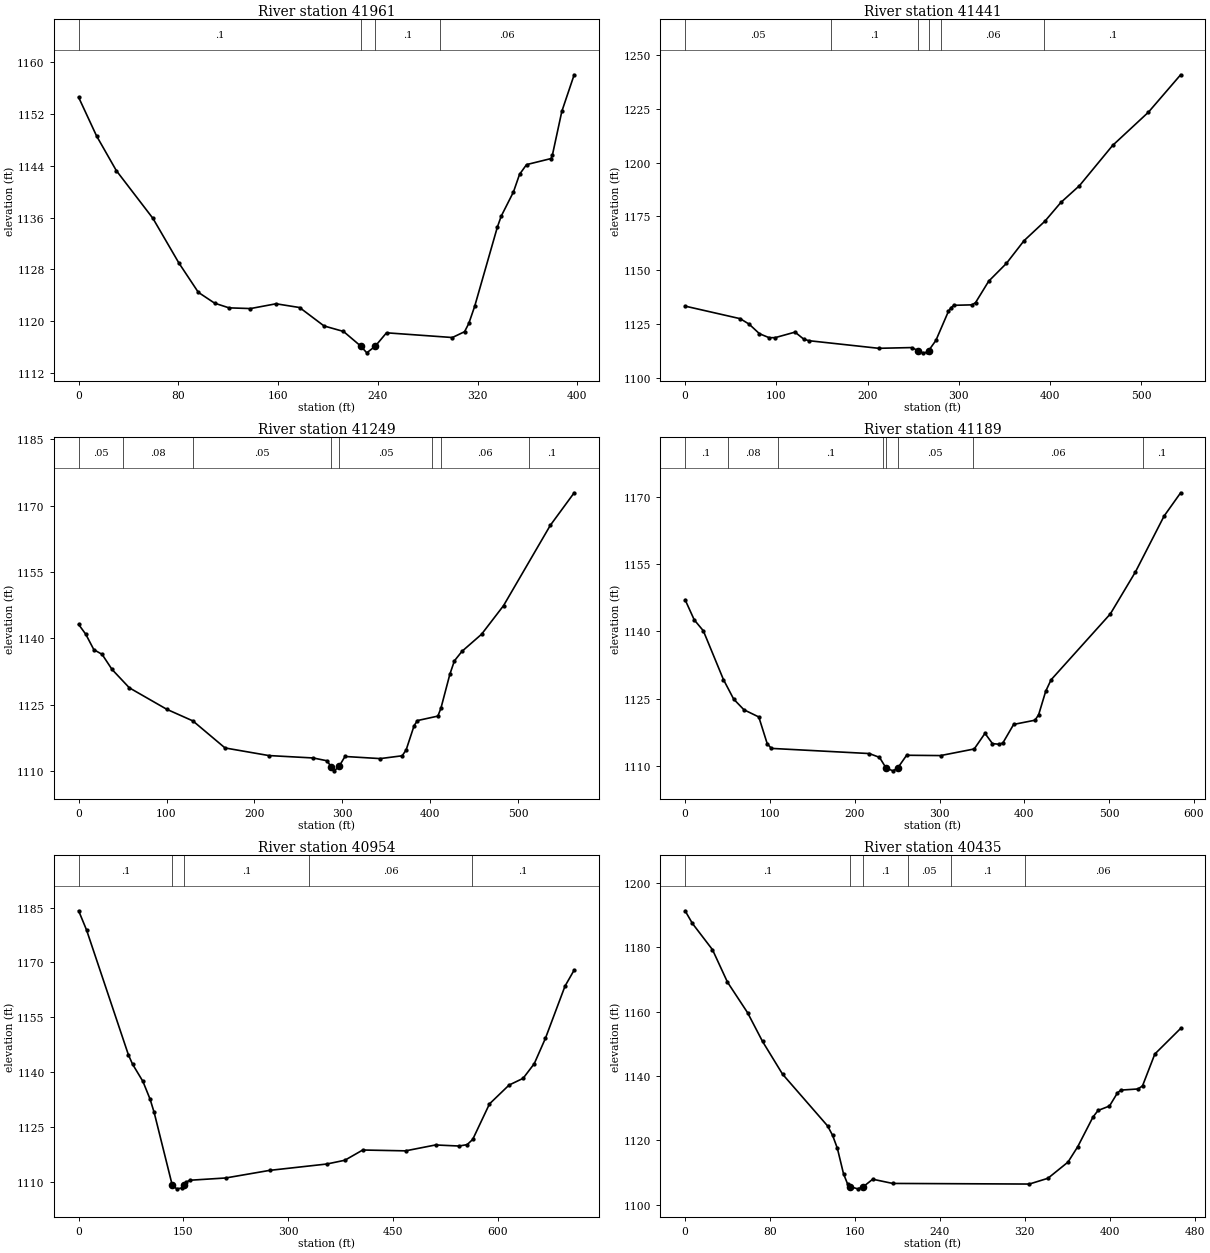
Type RM Length L Ch R = 1 ,41961   ,514.2,519.6,515.6
XS GIS Cut Line= 2
1673619.44969579 411853.074424551673943.88007704412082.635271932
#Sta/Elev= 30
       0 1154.61    14.4 1148.63    30.2 1143.28    59.6 1135.88    80.4 1128.98
      96 1124.44   109.1 1122.76   120.6 1122.04   137.8 1121.93   158.3 1122.67
   177.2 1122.09   196.8 1119.24   212.4 1118.39   226.2 1116.13   231.1 1115.08
   237.91116.117   246.9 1118.18   299.7 1117.45   309.5 1118.35   312.9 1119.63
   317.6 1122.27   335.8 1134.53   338.9 1136.23   348.7 1139.97   353.6  1142.7
   359.2  1144.2   378.9 1145.14     380 1145.73   387.5 1152.44   397.4  1158.1
#Mann= 4 ,-1,0
       0      .1       0   226.2    .045       0   237.9      .1       0
     290     .06       0
Bank Sta=226.2,237.9
XS Rating Curve= 0 ,0
Exp/Cntr(USF)=0,0
Exp/Cntr=0.3,0.1

Type RM Length L Ch R = 1 ,41441   ,187.8,192,196.6
XS GIS Cut Line= 4
1673449.99560266412223.9345469691673519.40175455412309.246275336
1673746.41770969412462.5181940971673892.45982097412526.140499998
#Sta/Elev= 30
       0 1133.29    60.4 1127.44    70.2  1124.9    81.5 1120.45    92.1  1118.6
    98.6 1118.61   120.5 1121.19   130.2 1117.87   135.9 1117.19   212.2 1113.66
   248.3    1114   255.6 1112.56   260.5 1111.55   265.3 1111.73  266.991112.608
   274.9 1117.31   288.6  1130.8   291.5 1132.57   294.6 1133.66   314.5 1133.88
   318.4 1134.93   332.8 1144.89   352.2 1153.16   371.5 1163.71   394.5 1172.83
   411.9 1181.51   432.3 1189.33   468.6 1208.03   507.9 1223.52   543.2 1240.92
#Mann= 6 ,-1,0
       0     .05       0  159.98      .1       0   255.6    .045       0
  266.99      .1       0  279.98     .06       0  393.89      .1       0
Bank Sta=255.6,266.99
XS Rating Curve= 0 ,0
Exp/Cntr(USF)=0,0
Exp/Cntr=0.3,0.1

Type RM Length L Ch R = 1 ,41249   ,59.4,60,60.7
XS GIS Cut Line= 5
1673368.15388503412282.6990746861673473.42584831412392.450695973
1673510.00972207412488.0167335571673518.22242842412585.822600146
1673705.62145525412683.628466735
#Sta/Elev= 30
       0 1143.14     8.1 1140.93    17.3 1137.44    26.7 1136.37      38 1132.96
    57.7  1128.8   100.3 1123.94     130 1121.31   166.6 1115.19   216.4 1113.47
     267 1112.92   282.8 1112.28     287 1110.99   291.1 1110.01   296.71111.132
   303.1 1113.26   343.2 1112.78   368.2 1113.42   372.7 1114.75   381.8 1120.26
   385.6 1121.39   408.8  1122.4   412.3  1124.2   422.4 1131.84   427.6  1134.9
   436.2 1137.05   458.5 1140.92   483.5 1147.39   536.8 1165.59   563.9 1172.94
#Mann= 8 ,-1,0
       0     .05       0      50     .08       0     130     .05       0
     287    .045       0   296.7     .05       0  402.56      .1       0
  412.56     .06       0  512.56      .1       0
Bank Sta=287,296.7
XS Rating Curve= 0 ,0
Exp/Cntr(USF)=0,0
Exp/Cntr=0.3,0.1

Type RM Length L Ch R = 1 ,41189   ,237.3,235.8,224.2
XS GIS Cut Line= 6
1673331.57001127412326.0024354661673412.20385548412437.993885759
1673454.01399692412500.7090979231673453.26738725412573.876845448
1673451.77416792412606.7276708671673702.63501657 412691.84117309
#Sta/Elev= 30
       0 1147.05    10.8 1142.56    21.5 1140.13    45.2 1129.27    57.3 1124.91
    69.4 1122.54    86.9 1120.94    96.8    1115   101.7 1113.94   217.2 1112.79
   229.2 1111.94   237.11109.538   245.2 1108.94   250.7 1109.58   261.2 1112.41
   301.2 1112.34   340.9 1113.81   353.6 1117.29   362.4 1115.01   370.5 1114.85
   374.7 1115.16   387.4 1119.28   412.6 1120.22   416.9 1121.46   425.2 1126.67
   431.5 1129.21   501.4 1143.89     531 1153.24   564.8 1165.69   584.3 1170.87
#Mann= 8 ,-1,0
       0      .1       0      50     .08       0     110      .1       0
  233.37     .05       0   237.1    .045       0   250.7     .05       0
  339.43     .06       0  539.43      .1       0
Bank Sta=237.1,250.7
XS Rating Curve= 0 ,0
Exp/Cntr(USF)=0,0
Exp/Cntr=0.3,0.1

Type RM Length L Ch R = 1 ,40954   ,516.9,518.1,518.3
XS GIS Cut Line= 3
1673155.37012948412381.2515509441673435.34875521412724.691998509
1673701.14179724412712.746243811
#Sta/Elev= 30
       0 1184.11    11.4 1178.82    71.3 1144.68    77.1 1142.18      92 1137.44
   102.3 1132.56   108.1 1128.94   133.9 1109.12   140.4 1108.06   147.9  1108.3
     1511109.039   153.9 1109.89   159.1 1110.41   210.4 1111.03   273.4 1113.11
   355.2 1114.85     381 1115.88   406.6 1118.68   467.9 1118.45   510.8 1120.06
   544.4 1119.77     556 1120.15     564 1121.58     588 1131.29     616 1136.44
   636.1 1138.28   652.1  1142.3   668.1 1149.25   696.1 1163.51   709.2  1167.9
#Mann= 5 ,-1,0
       0      .1       0   133.9    .045       0     151      .1       0
     330     .06       0   563.1      .1       0
Bank Sta=133.9,151
XS Rating Curve= 0 ,0
Exp/Cntr(USF)=0,0
Exp/Cntr=0.3,0.1

Type RM Length L Ch R = 1 ,40435   ,312.8,312.5,311.9
XS GIS Cut Line= 2
1672736.45644523412634.6718152881672983.58572481413030.547154141
#Sta/Elev= 30
       0 1191.38     6.9 1187.44    25.8 1179.28    39.9  1169.2    58.8 1159.72
    72.9 1150.78    91.8 1140.58   134.2  1124.5   138.9 1121.58   143.4 1117.54
   149.2 1109.62   153.1 1106.39   155.51105.626   162.5 1104.94     1681105.644
   176.7 1107.93   195.5 1106.62   324.2 1106.43   341.7 1108.22   360.6 1113.25
   369.8 1118.05   384.1 1127.23   388.9  1129.3   399.7 1130.69   407.2 1134.77
   410.4 1135.63   426.6 1135.99   430.8 1136.96   442.4 1146.85   466.7 1154.81
#Mann= 6 ,-1,0
       0      .1       0   155.5    .045       0     168      .1       0
     210     .05       0     250      .1       0     320     .06       0
Bank Sta=155.5,168
XS Rating Curve= 0 ,0
Exp/Cntr(USF)=0,0
Exp/Cntr=0.3,0.1

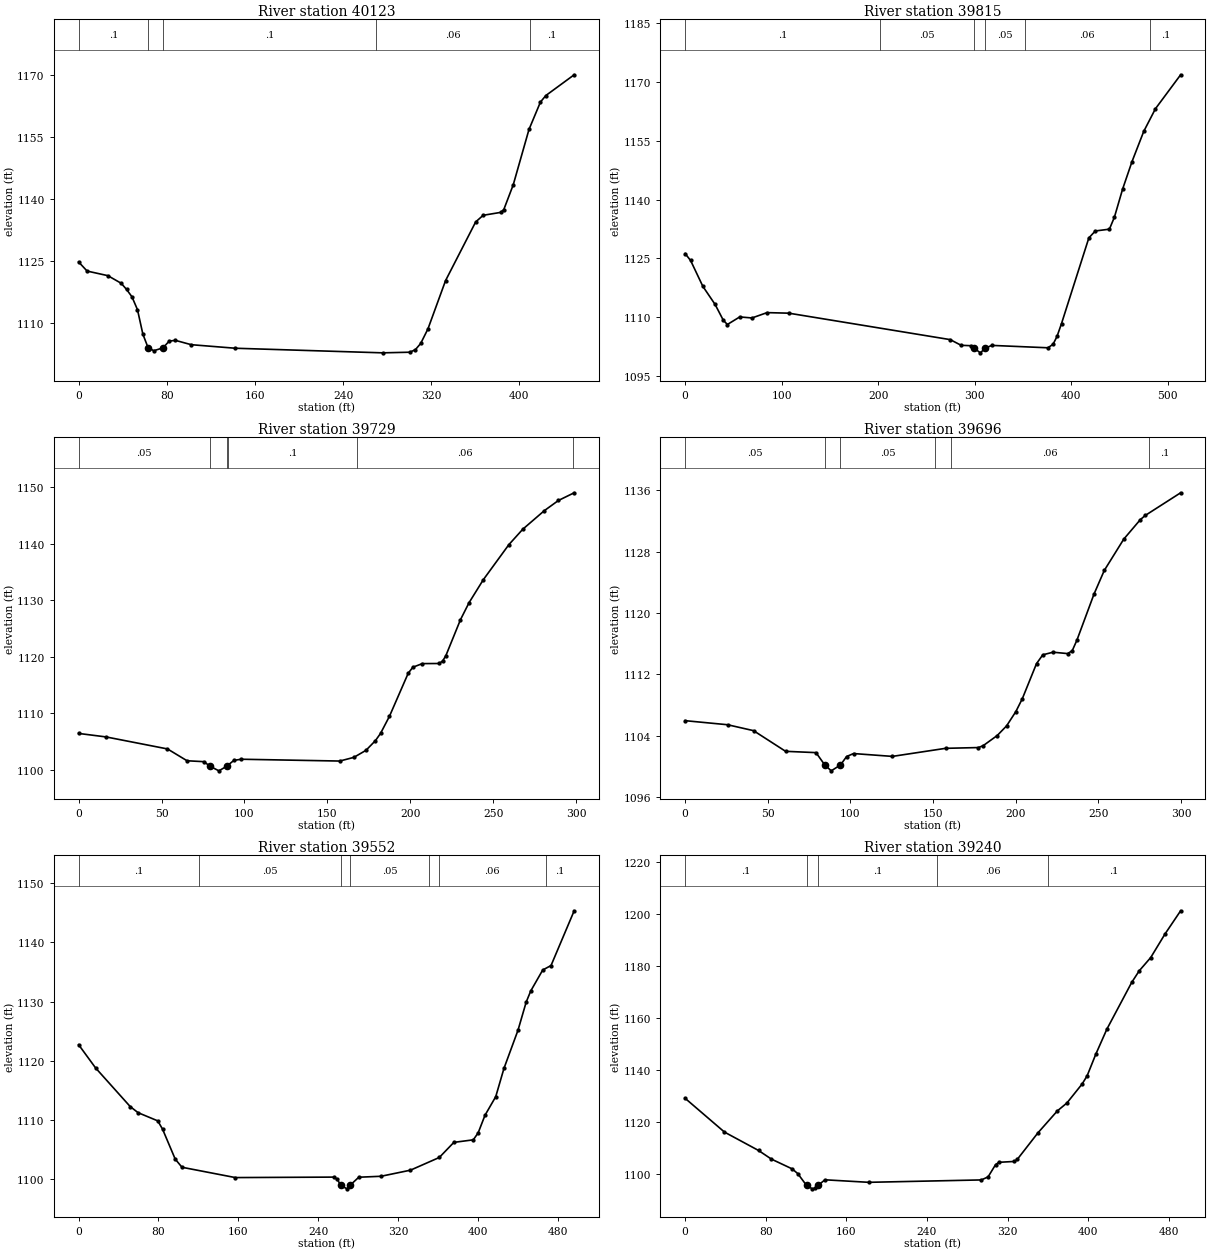
Type RM Length L Ch R = 1 ,40123   ,305.8,307.7,301.3
XS GIS Cut Line= 2
1672512.53845996412873.3282972311672776.61541358413237.285070202
#Sta/Elev= 30
       0 1124.84     7.7 1122.64    26.5 1121.53    38.6 1119.69    43.5  1118.2
    48.4 1116.41    53.4  1113.3    58.3 1107.3862.951261104.149    68.2 1103.37
76.551251104.067    82.2  1105.7    87.8 1105.88   102.2 1104.83   142.3 1103.97
   275.8 1102.86   300.5 1103.01   305.6 1103.63   310.4 1105.12     317 1108.65
     333 1120.34   360.3 1134.52   367.1 1136.13   382.9 1136.83   385.8 1137.49
   394.4  1143.5   408.7  1156.9   419.1 1163.53     424  1165.1   449.7 1170.12
#Mann= 5 ,-1,0
       0      .1       062.95126    .045       076.55125      .1       0
     270     .06       0     410      .1       0
Bank Sta=62.95126,76.55125
XS Rating Curve= 0 ,0
Exp/Cntr(USF)=0,0
Exp/Cntr=0.3,0.1

Type RM Length L Ch R = 1 ,39815   ,84.2,86.4,88.1
XS GIS Cut Line= 3
1672381.31753242412923.1610270751672438.16439259413085.235053939
1672695.78952484413309.598725456
#Sta/Elev= 30
       0 1126.24     5.7 1124.47    18.4 1117.87    31.1 1113.25    39.6 1109.22
    43.8 1108.14    56.6 1110.07    69.3 1109.81    84.9 1111.17   107.4 1111.03
   274.7 1104.28     286 1102.83   296.3 1102.73  299.46  1102.1   305.9 1100.91
   310.8 1102.06   317.6 1102.81   375.9  1102.2   381.2 1103.09   385.3 1105.08
     390 1108.39   418.3 1130.23     425    1132   439.6 1132.46   444.8 1135.53
   453.3  1142.7     463 1149.69   475.2 1157.42   487.3 1163.19   513.4 1171.85
#Mann= 6 ,-1,0
       0      .1       0  201.75     .05       0  299.46    .045       0
   310.8     .05       0  351.75     .06       0  481.75      .1       0
Bank Sta=299.46,310.8
XS Rating Curve= 0 ,0
Exp/Cntr(USF)=0,0
Exp/Cntr=0.3,0.1

Type RM Length L Ch R = 1 ,39729   ,32.9,32.7,32.4
XS GIS Cut Line= 4
 1672434.2605352413153.8819962861672483.43321712413246.002970019
1672497.74931439413287.083944792 1672598.3488325413399.683939835
#Sta/Elev= 30
       0 1106.45    16.6 1105.83    53.6 1103.71    65.4 1101.62    75.6 1101.46
   79.071100.684    84.6 1099.84    89.2 1100.63    93.7  1101.7    98.2 1101.89
   157.5 1101.57     166 1102.22   173.3 1103.46     179 1105.17   182.1 1106.45
   187.5 1109.49   198.8 1117.09   201.6 1118.15   207.3 1118.79   217.5 1118.81
   219.6 1119.27   221.5 1120.19   230.3 1126.54   235.5 1129.56   244.1 1133.62
   259.5 1139.81   267.9 1142.54   280.9 1145.82   289.4 1147.62   298.9 1148.98
#Mann= 6 ,-1,0
       0     .05       0   79.07    .045       0    89.2     .05       0
      90      .1       0  167.93     .06       0  297.93      .1       0
Bank Sta=79.07,89.2
XS Rating Curve= 0 ,0
Exp/Cntr(USF)=0,0
Exp/Cntr=0.3,0.1

Type RM Length L Ch R = 1 ,39696   ,144,144.1,143.2
XS GIS Cut Line= 5
 1672407.0306495413165.095080669  1672433.795527413224.226786782
1672463.67259956413275.2667857411672469.89698968413301.409224233
1672565.85417818 413415.18186312
#Sta/Elev= 30
       0 1105.99    25.7 1105.46    41.4 1104.69    60.8    1102    79.2 1101.83
    84.4 1100.26    88.4 1099.46      941100.222    97.7 1101.32   101.9 1101.71
   125.4 1101.34   157.6 1102.39   177.4 1102.49   180.3 1102.73   188.8 1104.05
   194.5 1105.31   200.1 1107.17     204 1108.84   212.6 1113.41   216.4 1114.56
   222.6  1114.9   231.4 1114.72   234.2 1115.09     237 1116.44   247.4 1122.47
   253.6 1125.54   265.4 1129.62   275.4 1132.15   278.4  1132.7   299.8 1135.65
#Mann= 6 ,-1,0
       0     .05       0    84.4    .045       0      94     .05       0
  150.92      .1       0  160.92     .06       0  280.92      .1       0
Bank Sta=84.4,94
XS Rating Curve= 0 ,0
Exp/Cntr(USF)=0,0
Exp/Cntr=0.3,0.1

Type RM Length L Ch R = 1 ,39552   ,309.7,312.4,310.4
XS GIS Cut Line= 4
1672164.49871069413120.1689425721672218.99283304413165.819476707
1672416.67459925413451.0694133821672396.49981049413526.999814259
#Sta/Elev= 30
       0 1122.73      17 1118.81    51.7 1112.29    59.6 1111.26    79.3 1109.88
    84.1 1108.49    96.8 1103.43   103.6 1102.05   157.1 1100.31   255.6 1100.39
   259.3 1100.03   262.7 1098.98   269.1 1098.41   272.2 1099.03   280.8 1100.37
   303.1 1100.53   332.6 1101.56   361.5  1103.7   376.1 1106.25   395.6 1106.68
   400.5 1107.87   407.3 1110.82   418.1 1113.97   426.3 1118.72   440.4 1125.18
   448.6 1129.92   453.2 1131.81   465.2 1135.34   473.5 1136.09   496.7 1145.33
#Mann= 7 ,-1,0
       0      .1       0  121.09     .05       0   262.7    .045       0
   272.2     .05       0  351.09      .1       0  361.09     .06       0
  468.14      .1       0
Bank Sta=262.7,272.2
XS Rating Curve= 0 ,0
Exp/Cntr(USF)=0,0
Exp/Cntr=0.3,0.1

Type RM Length L Ch R = 1 ,39240   ,294.8,294.2,293.5
XS GIS Cut Line= 3
1671988.21888457413286.5427661511672180.30040993413596.918401642
1672254.08782516413699.986537202
#Sta/Elev= 30
       0 1129.24    39.1 1116.23    72.9 1109.16    85.6 1105.85   106.2 1102.09
   111.8 1100.27   120.5 1095.73   126.3  1094.4   129.4 1094.61   132.1 1095.77
   138.8 1097.88   182.2 1096.91     294 1097.83   300.7    1099   308.1 1103.69
   311.4 1104.61   326.9 1104.94   329.7 1105.74   350.1 1115.91   369.5 1124.41
   378.9 1127.42   394.1 1134.78     399 1137.89   407.6  1146.2   418.6 1155.85
   443.2  1173.8   450.7 1178.29   462.1 1183.39   476.4 1192.53   491.8 1201.39
#Mann= 5 ,-1,0
       0      .1       0   120.5    .045       0   132.1      .1       0
     250     .06       0     360      .1       0
Bank Sta=120.5,132.1
XS Rating Curve= 0 ,0
Exp/Cntr(USF)=0,0
Exp/Cntr=0.3,0.1

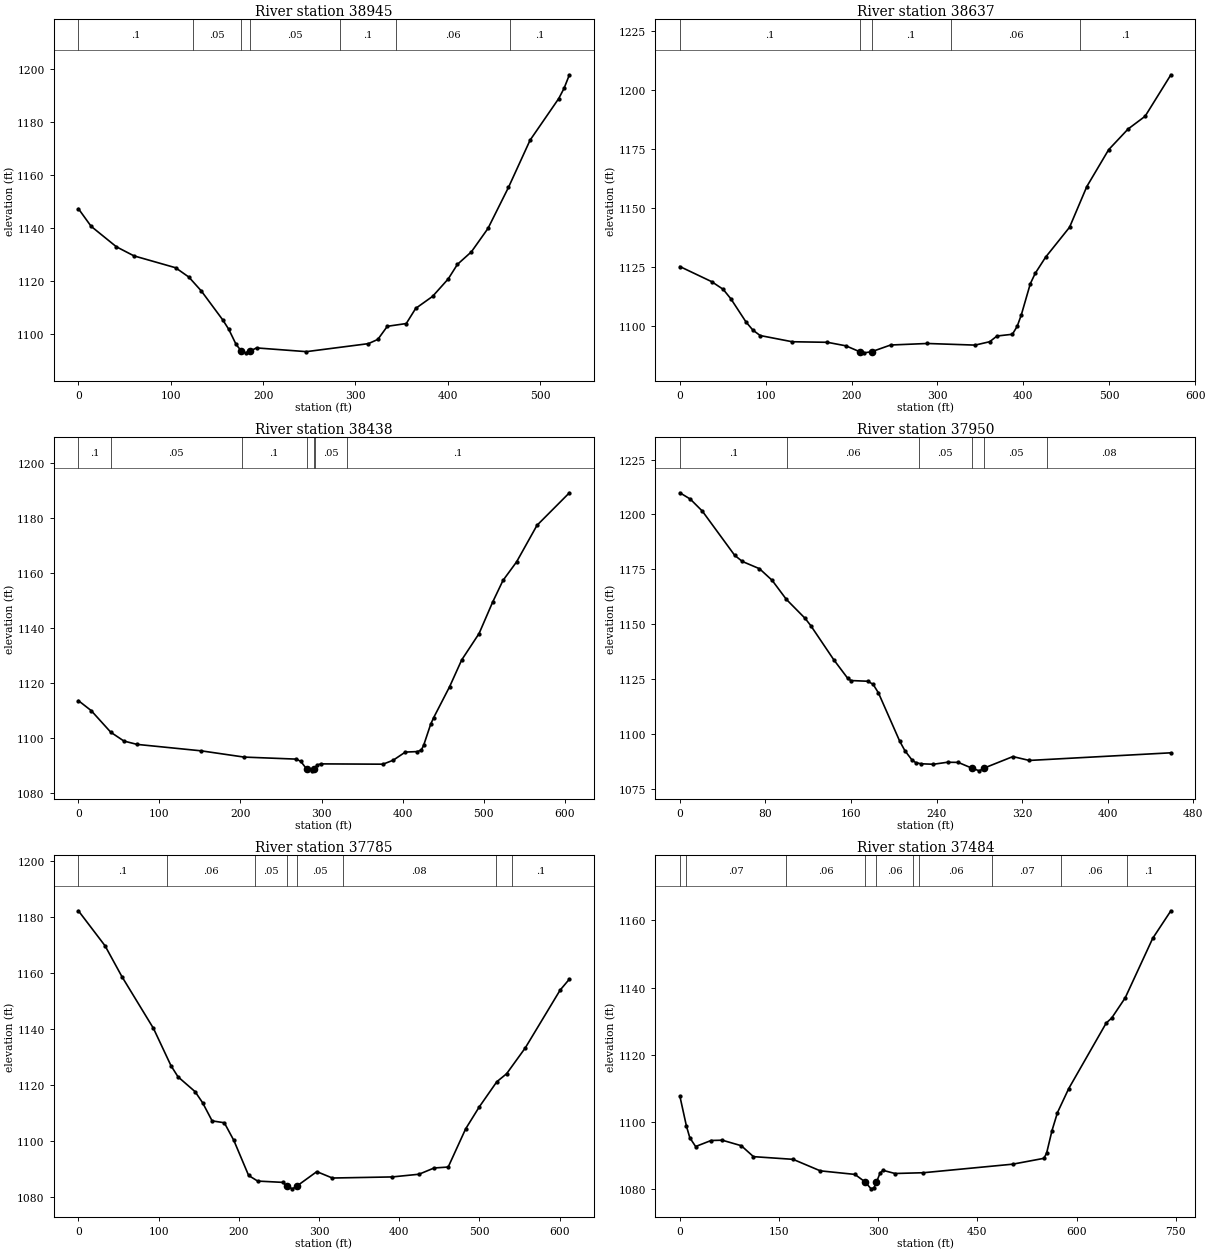
Type RM Length L Ch R = 1 ,38945   ,312.8,308.6,304.9
XS GIS Cut Line= 4
1671722.40800282413416.4583780431671777.45575704413516.012827163
1671935.57164682413713.9504965891672035.12609594413845.128123664
#Sta/Elev= 30
       0 1147.17    13.8 1140.51    41.2 1132.78    60.2 1129.36   105.2 1124.89
   119.6 1121.37   133.1 1116.13   156.5 1105.12   162.9 1101.61   170.7    1096
   176.5  1093.4     181 1092.76   186.1 1093.45   192.9 1094.62   246.9 1093.21
   314.1 1096.23   324.3 1097.83   334.6 1102.78   355.1 1103.82   365.3 1109.53
   383.6 1114.07   400.5 1120.64   410.5 1126.15   425.6 1130.87   443.6 1139.72
   465.8 1155.21   489.2 1173.04   520.2 1188.73     526 1192.61   531.8 1197.72
#Mann= 7 ,-1,0
       0      .1       0  123.76     .05       0   176.5    .045       0
   186.1     .05       0  283.76      .1       0  343.76     .06       0
   467.1      .1       0
Bank Sta=176.5,186.1
XS Rating Curve= 0 ,0
Exp/Cntr(USF)=0,0
Exp/Cntr=0.3,0.1

Type RM Length L Ch R = 1 ,38637   ,195.7,198.5,199.6
XS GIS Cut Line= 6
1671417.89652128413595.6104361081671500.54621159413705.810023196
1671550.27041552413725.9684842491671590.58733763413740.079406985
 1671617.4652857413756.8781245291671835.84861377 413971.22976039
#Sta/Elev= 30
       0 1125.23      37 1118.82    50.4 1115.57    59.4 1111.53      77 1101.71
    85.1 1098.23    93.5 1095.95   130.8 1093.32   171.8 1093.08   193.4 1091.58
   209.8 1089.02   214.5 1088.61   223.21089.075   245.4 1091.93   288.2 1092.58
   343.8 1091.89   360.8 1093.33   369.3 1095.75   387.2 1096.49   392.8 1099.85
   397.6 1104.71   408.1 1117.95   413.8 1122.34   425.8 1129.16   453.8 1141.91
   473.9 1159.18   499.3 1174.81     522 1183.61   541.8 1189.01   571.8 1206.61
#Mann= 5 ,-1,0
       0      .1       0   209.8    .045       0   223.2      .1       0
  315.82     .06       0  465.82      .1       0
Bank Sta=209.8,223.2
XS Rating Curve= 0 ,0
Exp/Cntr(USF)=0,0
Exp/Cntr=0.3,0.1

Type RM Length L Ch R = 1 ,38438   ,487.4,487.9,486.8
XS GIS Cut Line= 4
1671330.74844505413660.8194446661671349.54594452413811.199440432
1671609.81901411414003.5123196321671734.17170292414043.999241569
#Sta/Elev= 30
       0 1113.54    15.8 1109.91      40 1102.03    56.2 1098.84    72.3 1097.63
   151.6 1095.28   204.5 1093.01   269.1 1092.27   274.5 1091.41   281.7 1088.67
   288.4 1088.01   290.7 1088.71   294.5 1090.09     299 1090.54   375.9 1090.43
   388.5 1091.88   403.4 1094.83   418.3 1095.01   423.2 1095.59   426.1 1097.35
   434.6 1104.87   438.2 1107.25   458.1 1118.63     473 1128.35   494.4 1137.93
   511.2 1149.38   523.9 1157.23   540.7 1163.99   565.9 1177.29   605.9 1189.12
#Mann= 7 ,-1,0
       0      .1       0      40     .05       0  201.55      .1       0
   281.7    .045       0   290.7      .1       0  291.55     .05       0
  331.55      .1       0
Bank Sta=281.7,290.7
XS Rating Curve= 0 ,0
Exp/Cntr(USF)=0,0
Exp/Cntr=0.3,0.1

Type RM Length L Ch R = 1 ,37950   ,165.2,164.7,162.1
XS GIS Cut Line= 3
1670928.35679633414078.6517312741671058.36319459414193.432154965
1671287.92404198414363.260332875
#Sta/Elev= 30
       0 1209.85     9.7 1206.98      21 1201.49    51.2 1181.36    58.4 1178.54
    74.4 1175.24    86.2 1169.97    99.5 1161.28   117.1 1152.59   122.4 1149.26
   143.7 1133.85     157 1125.21   159.9 1124.26   175.6 1123.94   180.6 1122.56
   185.6 1118.65   205.5 1096.62   210.4 1092.25   216.9  1088.1   220.4 1086.88
   225.4 1086.32     237  1086.1   250.2 1087.02   260.2 1086.95   272.8 1084.36
   279.9  1083.1  284.511084.383   311.3  1089.6   326.6 1087.84     459 1091.32
#Mann= 6 ,-1,0
       0      .1       0     100     .06       0  223.42     .05       0
   272.8    .045       0  284.51     .05       0  343.42     .08       0
Bank Sta=272.8,284.51
XS Rating Curve= 0 ,0
Exp/Cntr(USF)=0,0
Exp/Cntr=0.3,0.1

Type RM Length L Ch R = 1 ,37785   ,309,301.3,293.5
XS GIS Cut Line= 2
1670798.51489092414274.2733448531671358.47214239414521.484101796
#Sta/Elev= 30
       0 1182.26    33.3 1169.73    54.2 1158.79    93.6 1140.28   115.4 1126.99
   124.2 1123.01   145.5 1117.71   154.8 1113.78   166.7 1107.29   181.9 1106.62
   193.8  1100.3   212.2 1087.81   223.5 1085.81   254.7 1085.35   259.7 1084.09
   266.8 1083.04   272.7  1084.1   297.2 1089.18   316.6  1086.9   391.2 1087.29
   424.6 1088.25   443.4 1090.48     461 1090.82   482.7 1104.42   499.7 1112.27
   521.6 1121.26   533.8 1124.11   557.1 1133.34   600.5 1153.95   612.1 1157.88
#Mann= 8 ,-1,0
       0      .1       0     110     .06       0     220     .05       0
   259.7    .045       0   272.7     .05       0     330     .08       0
     520     .06       0     540      .1       0
Bank Sta=259.7,272.7
XS Rating Curve= 0 ,0
Exp/Cntr(USF)=0,0
Exp/Cntr=0.3,0.1

Type RM Length L Ch R = 1 ,37484   ,51.2,51.1,50.6
XS GIS Cut Line= 5
1670695.49242458414752.3343552171670869.16812175414653.012579642
1670986.35143394414591.5107025631671139.36032899414488.275785421
1671359.57328701414537.977244054
#Sta/Elev= 30
       0 1107.71     9.9 1098.83      15 1095.37    23.8 1092.75    47.2 1094.54
    64.1 1094.63    92.9 1092.99   111.3 1089.74   171.2 1088.94   212.4 1085.52
   264.8 1084.46   280.2 1082.22   289.2 1080.17   293.7 1080.51297.37541082.168
   302.8 1084.86   307.3 1085.67   325.4 1084.73   368.3 1084.96   503.4  1087.5
   550.6 1089.24   554.7 1090.77   562.9 1097.51   571.1 1102.82   588.1 1109.95
   644.9 1129.47   653.1 1130.93   673.6 1136.95   715.2 1154.64   742.7 1162.83
#Mann= 10 ,-1,0
       0     .06       0      10     .07       0     160     .06       0
   280.2    .045       0297.3754     .06       0  352.41     .07       0
  362.41     .06       0  472.41     .07       0  576.99     .06       0
  676.99      .1       0
Bank Sta=280.2,297.3754
XS Rating Curve= 0 ,0
Exp/Cntr(USF)=0,0
Exp/Cntr=0.3,0.1