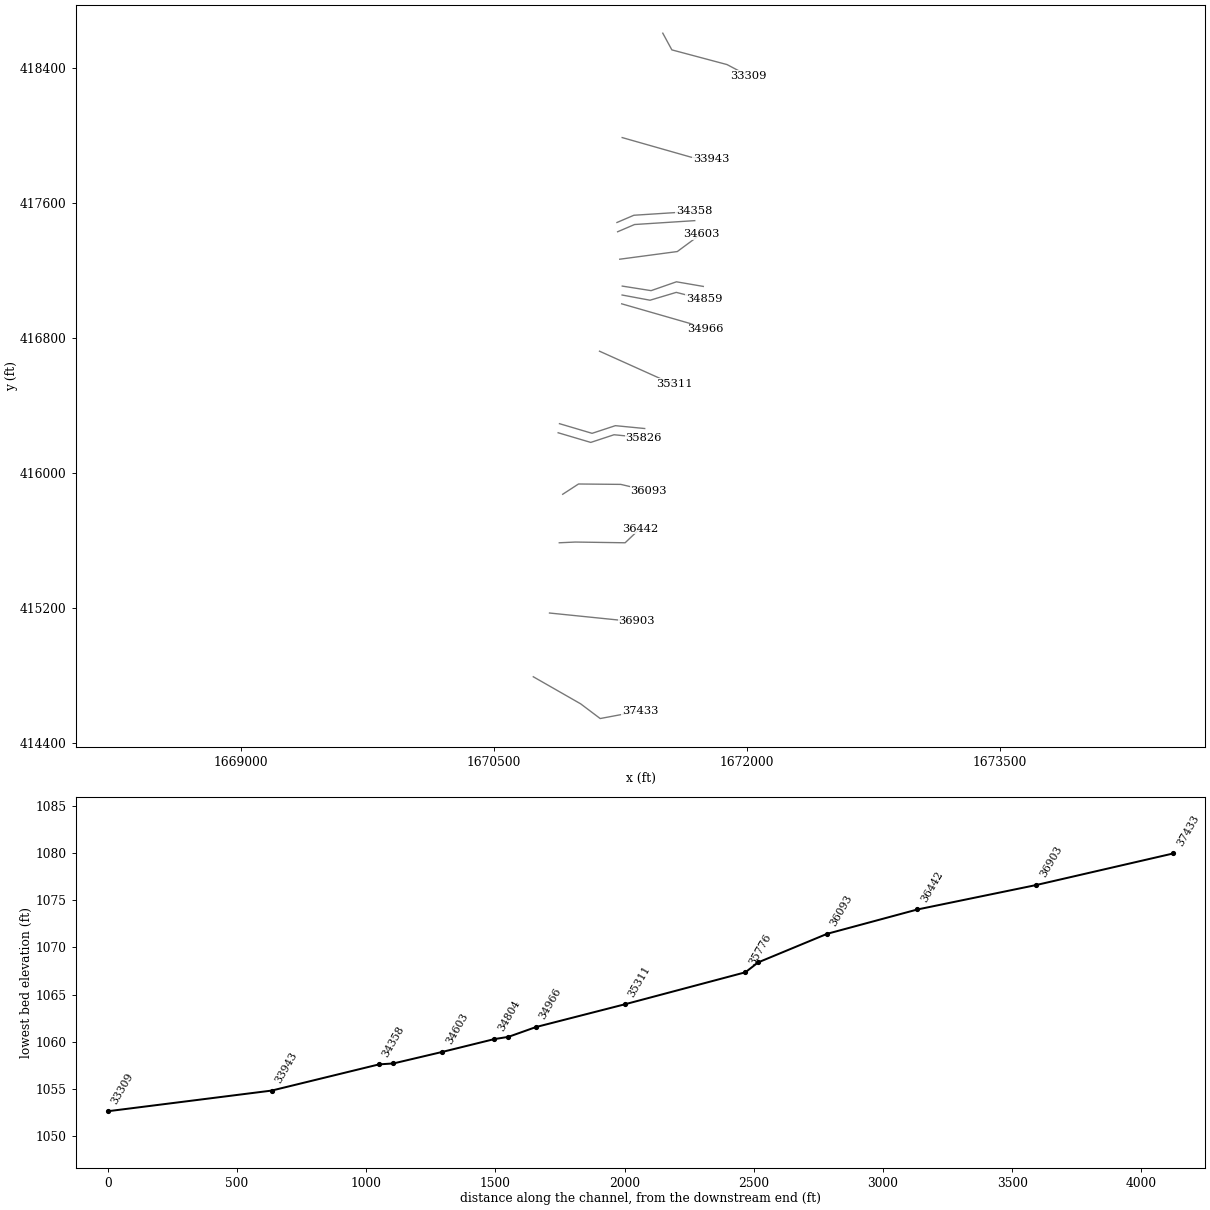
HEC-RAS study KNOBBFK.prj: KNOBBFK

--- KNOBBFK.g01 (geometry) --- (continued)

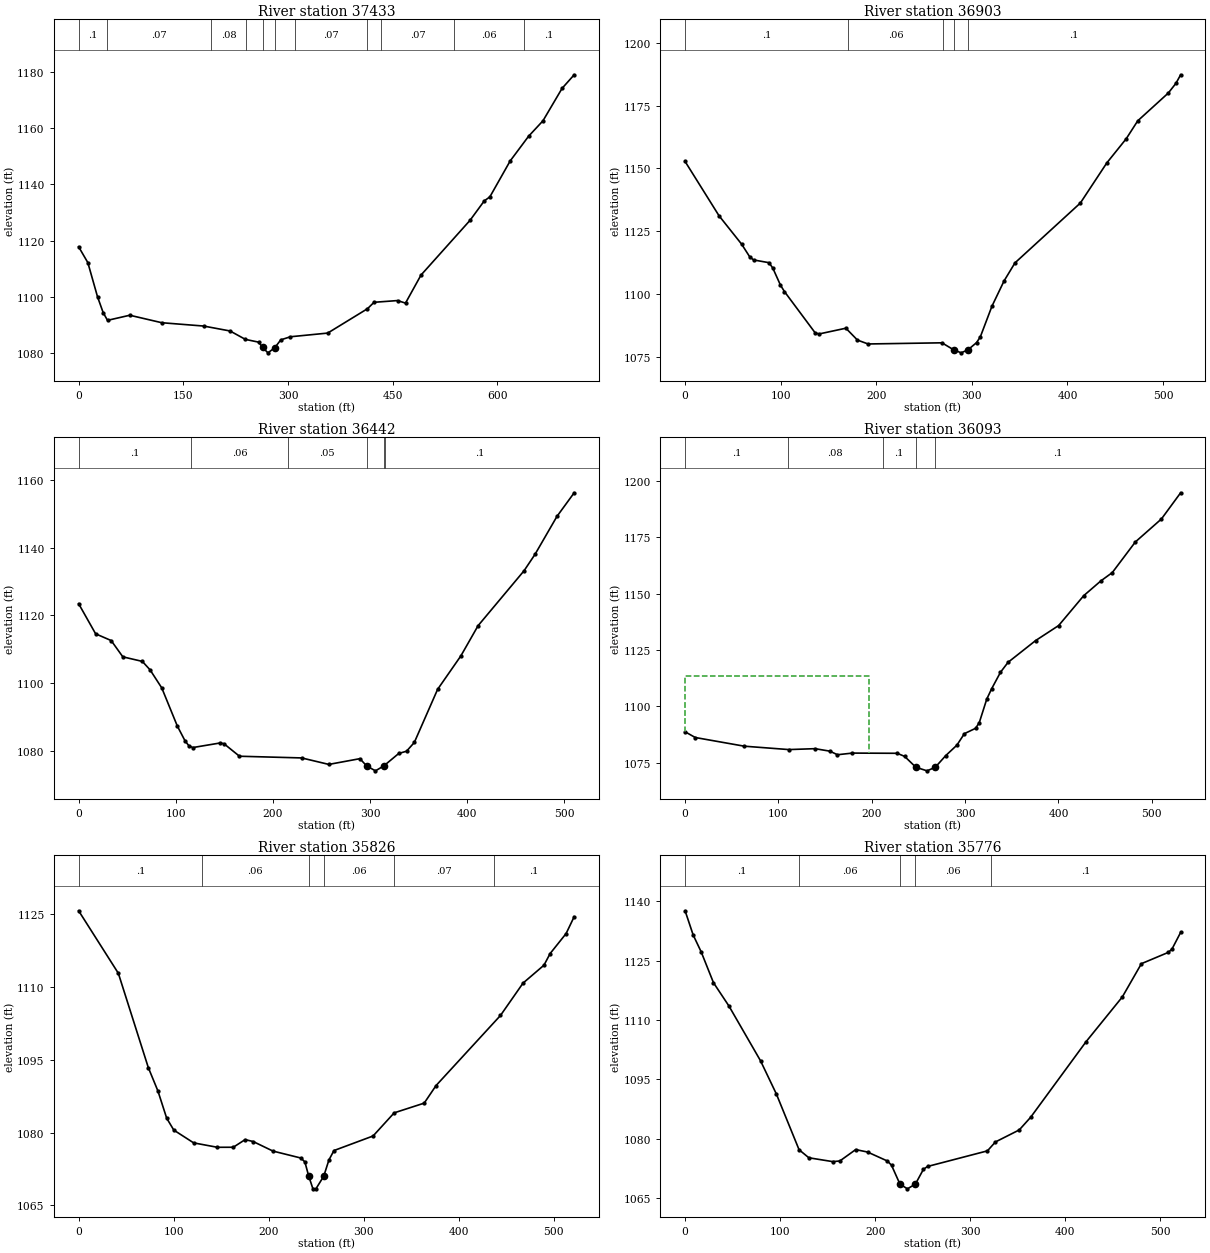
Type RM Length L Ch R = 1 ,37433   ,526.1,530.4,533
XS GIS Cut Line= 4
1670732.62477608414793.0930280171671013.36981323414632.604787403
1671129.22118534414545.4236859821671366.78020953414590.052937745
#Sta/Elev= 30
       0 1117.76    13.2 1112.12    27.1 1099.92    35.2 1094.28    41.4 1091.55
    73.3 1093.37   119.2  1090.7   179.1 1089.52     217 1087.76     239 1084.76
     258 1083.78   263.51081.897   271.3 1079.97281.01591081.776   289.7  1084.6
   303.5  1085.7   356.9 1087.01   413.9 1095.69   423.3 1097.98     457  1098.6
   468.4 1097.69   490.6 1107.68   560.9  1127.2   581.2  1134.1   589.3 1135.56
   618.4 1148.36   644.8 1157.16   665.4 1162.67   692.8 1174.23   710.1 1179.06
#Mann= 11 ,-1,0
       0      .1       0      40     .07       0     190     .08       0
     240     .06       0   263.5    .045       0281.0159     .06       0
     310     .07       0  413.38     .06       0  433.38     .07       0
  538.37     .06       0  638.37      .1       0
Bank Sta=263.5,281.0159
XS Rating Curve= 0 ,0
Exp/Cntr(USF)=0,0
Exp/Cntr=0.3,0.1

Type RM Length L Ch R = 1 ,36903   ,459.2,460.9,461.2
XS GIS Cut Line= 3
1670828.78387063415170.9969243351671240.88289749  415129.0640409
1671344.99212533415126.172117905
#Sta/Elev= 30
       0 1152.76    35.5 1131.16    59.2 1119.83    67.7 1114.76    71.7 1113.58
    87.8 1112.49    91.8 1110.31    99.8 1103.53   103.9 1101.02     136 1084.61
     140 1084.12   168.2 1086.42   180.3  1081.7   191.4 1080.15   268.7 1080.61
   280.8 1077.86   288.8 1076.62   295.91077.826   304.9 1080.68   308.9 1083.03
     321 1095.17   333.7 1105.25   345.1 1112.42   413.5 1136.23   441.2 1152.21
   461.5 1161.82   473.5 1168.93   505.5    1180   513.5 1183.87   518.4 1187.26
#Mann= 5 ,-1,0
       0      .1       0     170     .06       0     270      .1       0
   280.8    .045       0   295.9      .1       0
Bank Sta=280.8,295.9
XS Rating Curve= 0 ,0
Exp/Cntr(USF)=0,0
Exp/Cntr=0.3,0.1

Type RM Length L Ch R = 1 ,36442   ,349.5,349.2,349.2
XS GIS Cut Line= 4
1670886.62233054415587.4338356851670982.05578939415591.771720178
1671277.03193493415587.433835685 1671363.7896248415669.853641057
#Sta/Elev= 30
       0 1123.47    17.5 1114.56    33.5 1112.57    45.5 1107.75    65.6  1106.4
    73.6 1103.88    85.6 1098.55   101.6 1087.28   109.6 1082.87   113.6 1081.41
   117.6 1080.91   145.6 1082.26   149.6 1082.05   165.6 1078.34   229.6 1077.84
   257.6 1075.92   289.6 1077.62   296.51075.483   305.6 1074.02   314.1 1075.46
   329.6 1079.16   337.6 1079.83   345.6 1082.41   369.6 1098.13   393.5 1108.01
   411.3 1116.98   458.6 1133.22   469.9 1138.08   492.5 1149.31   510.2 1156.29
#Mann= 6 ,-1,0
       0      .1       0  115.53     .06       0  215.53     .05       0
   296.5    .045       0   314.1     .05       0  315.53      .1       0
Bank Sta=296.5,314.1
XS Rating Curve= 0 ,0
Exp/Cntr(USF)=0,0
Exp/Cntr=0.3,0.1

Type RM Length L Ch R = 1 ,36093   ,263.5,266.8,269.2
XS GIS Cut Line= 4
1670906.99375794415875.0241112131671000.69206299415935.928009498
1671251.33502901415933.5855518711671415.30706285415894.935001037
#Sta/Elev= 30
       0 1088.76    10.9 1086.22    63.4 1082.37   111.1 1080.87   139.2 1081.27
   155.2 1080.16   163.2 1078.58   179.2 1079.31   227.2 1079.22   235.2 1077.85
   247.2 1073.04   259.2 1071.44     2681073.015   279.2 1078.18   291.2 1082.83
   299.2 1087.92   311.2  1090.3   315.2 1092.85   323.2 1103.27   328.5  1107.9
   337.9 1115.16     346 1119.56   375.5  1129.2   400.2 1135.87   427.1 1149.13
   445.4 1155.66   457.7 1159.37   482.4 1172.95   510.3 1183.13   530.9 1194.75
#Mann= 5 ,-1,0
       0      .1       0     110     .08       0  211.75      .1       0
   247.2    .045       0     268      .1       0
#XS Ineff= 2 , 0
          197.36 1113.62
Permanent Ineff=
       F       F
Bank Sta=247.2,268
XS Rating Curve= 0 ,0
Exp/Cntr(USF)=0,0
Exp/Cntr=0.3,0.1

Type RM Length L Ch R = 1 ,35826   ,49.5,49.5,49.5
XS GIS Cut Line= 4
1670880.00306528416239.6913006231671073.26286044416182.470553205
1671211.33196084 416227.897800771671385.27399168416210.985163111
#Sta/Elev= 30
       0 1125.64    41.8 1112.78    73.4 1093.34    83.5 1088.54    92.7 1082.95
   100.2  1080.5   121.1 1077.87   146.1 1076.96   162.8 1076.97   175.3 1078.54
   183.7 1078.15   204.6 1076.18     234 1074.75   238.2 1073.95   242.11071.114
   246.6 1068.45   249.8 1068.41  258.041071.007   263.5 1074.35   268.8 1076.29
     310 1079.29   332.2 1084.05   363.8 1086.05   376.3 1089.67   444.1 1104.09
   467.9 1110.76   489.9 1114.44   496.4 1116.84   513.2 1120.95   521.7 1124.42
#Mann= 6 ,-1,0
       0      .1       0     130     .06       0   242.1    .045       0
  258.04     .06       0  331.55     .07       0   436.9      .1       0
Bank Sta=242.1,258.04
XS Rating Curve= 0 ,0
Exp/Cntr(USF)=0,0
Exp/Cntr=0.3,0.1

Type RM Length L Ch R = 1 ,35776   ,469.4,465.7,458.9
XS GIS Cut Line= 4
1670887.93371075416293.5393732221671081.19350591416236.318625805
1671219.26260631416281.7458733691671393.20463714 416264.83323571
#Sta/Elev= 30
       0 1137.64     8.5 1131.52    16.9 1127.27    29.9 1119.45    46.1 1113.59
    79.4 1099.73    96.1 1091.33     120 1077.24   130.3 1075.21   155.4 1074.24
   162.9  1074.4   179.6 1077.28   192.1 1076.66     213 1074.39   217.3 1073.33
   226.2 1068.55   234.1 1067.36   242.5 1068.58   250.9 1072.29   255.2 1073.01
   318.3 1076.96   326.7 1079.21   351.8 1082.25   363.8 1085.45     422 1104.51
   460.3 1115.86   480.4 1124.27   508.5  1127.1   512.5 1127.92   521.7 1132.17
#Mann= 5 ,-1,0
       0      .1       0     120     .06       0   226.2    .045       0
   242.5     .06       0  321.55      .1       0
Bank Sta=226.2,242.5
XS Rating Curve= 0 ,0
Exp/Cntr(USF)=0,0
Exp/Cntr=0.3,0.1

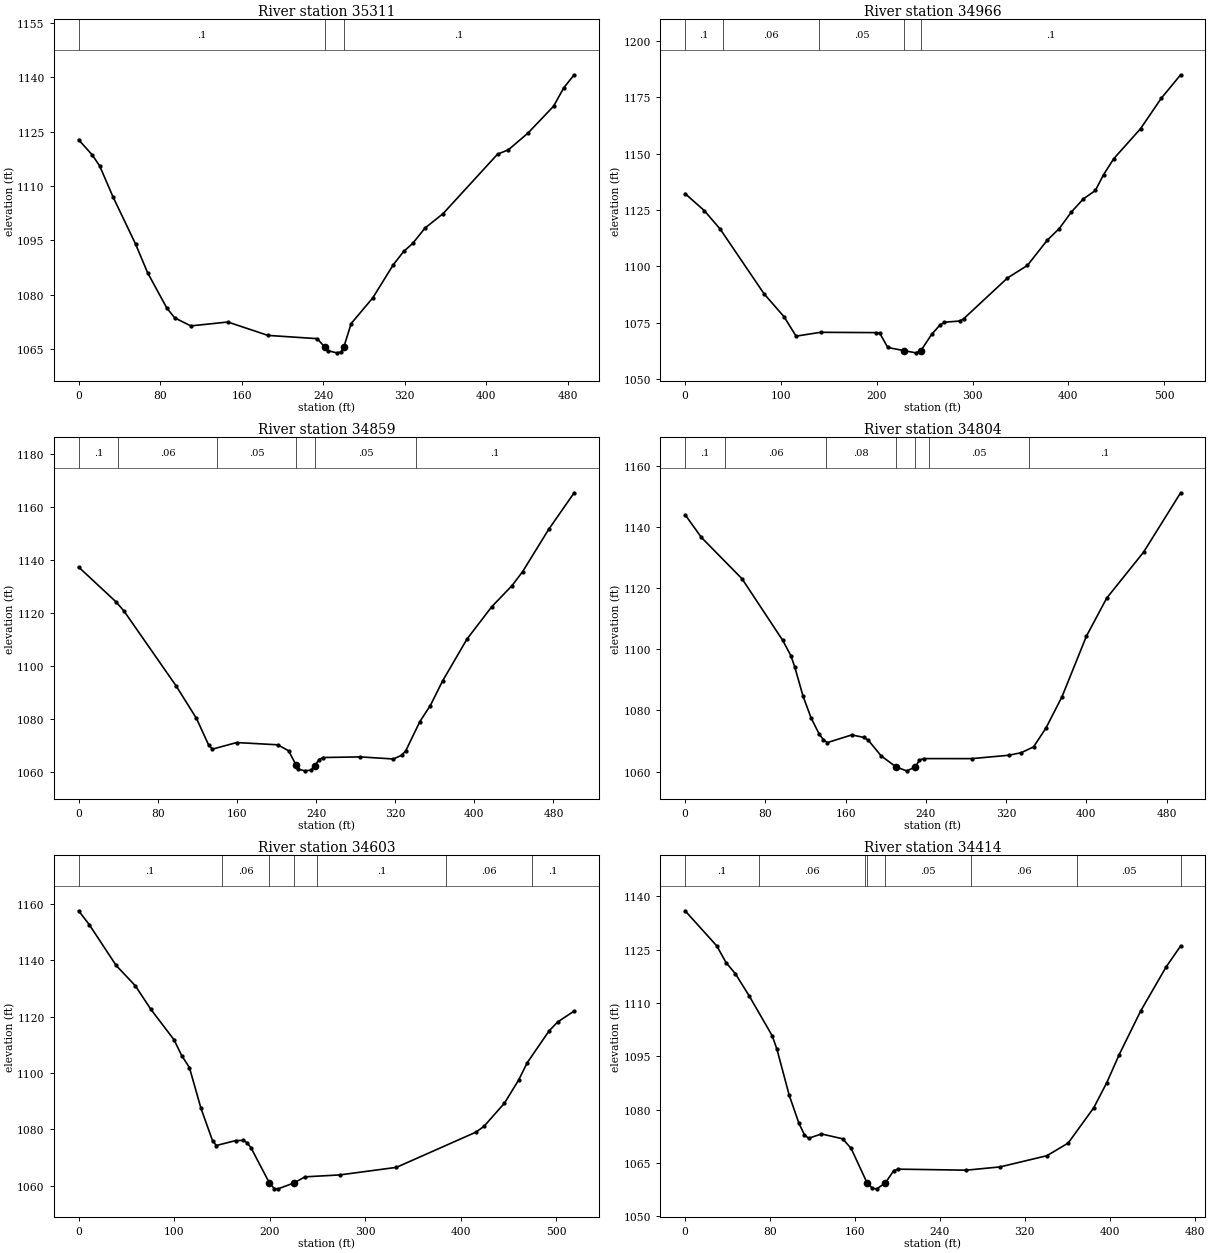
Type RM Length L Ch R = 1 ,35311   ,343.1,345,345.7
XS GIS Cut Line= 3
1671125.25600842416723.2406572781671510.59028795416549.898792928
1671571.49418624416531.159131918
#Sta/Elev= 30
       0 1122.71    13.3 1118.57    20.7 1115.48    33.8 1106.93    55.8 1094.01
    67.7 1086.04    86.5 1076.34    94.3  1073.6   110.1  1071.4   146.4 1072.47
   185.7 1068.78   234.1 1067.88   241.81065.463   244.4 1064.58   253.1 1063.97
   257.5 1064.21   260.1 1065.48   267.4 1072.05   288.6 1079.13   308.8 1088.29
   318.9 1091.92   327.7 1094.13     340 1098.41   357.6 1102.36     411 1118.74
   421.7 1119.96   440.8 1124.55     466 1131.97     476 1137.06   486.2 1140.64
#Mann= 3 ,-1,0
       0      .1       0   241.8    .045       0   260.1      .1       0
Bank Sta=241.8,260.1
XS Rating Curve= 0 ,0
Exp/Cntr(USF)=0,0
Exp/Cntr=0.3,0.1

Type RM Length L Ch R = 1 ,34966   ,99.3,106.5,109.8
XS GIS Cut Line= 3
1671256.81641699417004.1103566231671663.70130669416887.104598188
1671751.19209903416853.373208368
#Sta/Elev= 30
       0  1132.2    20.1 1124.64    36.7 1116.41    82.5 1087.69   103.3 1077.55
   115.8 1068.96   141.3 1070.66   199.5 1070.52   203.2 1070.19   211.5 1063.93
   228.2 1062.54   240.7 1061.55     2461062.487   257.3 1069.77   265.6 1073.71
   270.6 1075.14   286.5 1075.66   290.6 1076.64   336.4 1094.77   357.2 1100.34
     378 1111.58   390.5 1116.72     403 1124.01   415.5 1129.82   428.1  1133.6
   436.7 1140.62   447.3  1147.7   475.3 1161.04   496.8 1174.47   517.1 1184.94
#Mann= 5 ,-1,0
       0      .1       0      40     .06       0     140     .05       0
   228.2    .045       0     246      .1       0
Bank Sta=228.2,246
XS Rating Curve= 0 ,0
Exp/Cntr(USF)=0,0
Exp/Cntr=0.3,0.1

Type RM Length L Ch R = 1 ,34859   ,55,55,55.8
XS GIS Cut Line= 4
1671259.05834903417056.3203876651671424.62785304417025.459799639
1671580.40034498417071.9956069791671744.99014778417029.868455071
#Sta/Elev= 30
       0 1137.43    37.7 1124.33    45.8 1120.86    98.7 1092.48   119.1  1080.3
   131.3 1070.35   135.3 1068.71   159.8 1071.19   201.3 1070.34   212.3 1068.07
  219.861062.621   222.2 1061.15   228.6 1060.51   234.7 1060.79   238.9 1062.51
     243 1064.76   247.2 1065.54   284.8 1065.77   318.2 1064.98   326.5  1066.4
   330.7  1068.1   344.9 1079.09   355.5 1085.16   367.9 1094.45   392.6 1110.28
   417.4 1122.37   438.1 1130.44   448.7 1135.65   475.2  1151.7   500.9 1165.47
#Mann= 6 ,-1,0
       0      .1       0      40     .06       0     140     .05       0
  219.86    .045       0   238.9     .05       0     341      .1       0
Bank Sta=219.86,238.9
XS Rating Curve= 0 ,0
Exp/Cntr(USF)=0,0
Exp/Cntr=0.3,0.1

Type RM Length L Ch R = 1 ,34804   ,202.9,201.3,199.5
XS GIS Cut Line= 4
1671260.03805024417109.2242528521671430.99591089417082.282469654
1671581.38004619417134.6964842381671740.58149235417107.264850437
#Sta/Elev= 30
       0 1143.97    16.3 1136.53    56.8 1123.02    97.3 1102.91   105.4 1097.93
   109.4 1094.11   117.5 1084.72   125.6 1077.55   133.7 1072.24   137.8 1070.48
   141.8  1069.5   166.1 1072.01   178.5 1071.17   182.7 1070.23   195.4 1065.16
   210.51061.504   220.8 1060.27   229.3 1061.47   233.6 1063.78   237.8 1064.27
   285.7 1064.26   322.5 1065.36   335.1  1066.2   347.3  1068.1   359.5 1074.16
   375.7 1084.52     400 1104.29   420.3 1116.76   456.9 1131.71   493.9 1151.14
#Mann= 7 ,-1,0
       0      .1       0      40     .06       0     140     .08       0
   210.5    .045       0   229.3     .08       0  243.07     .05       0
  342.32      .1       0
Bank Sta=210.5,229.3
XS Rating Curve= 0 ,0
Exp/Cntr(USF)=0,0
Exp/Cntr=0.3,0.1

Type RM Length L Ch R = 1 ,34603   ,189.8,188.8,190
XS GIS Cut Line= 3
1671245.13083208417268.5724436511671586.51614009417314.090484719
1671726.86343338417417.770467152
#Sta/Elev= 30
       0 1157.62    11.1 1152.72    39.3 1138.21    59.4 1130.99    75.6 1122.65
    99.9 1111.82   107.9 1106.24     116 1101.98   128.1  1087.5   140.2 1076.02
   144.2 1074.29   164.4 1076.04   172.5  1076.1   176.5 1075.26   180.6 1073.42
  199.721061.021   204.8 1059.01   208.8 1058.91     225 1060.93   237.1 1063.17
   273.4 1063.85   332.7 1066.53     416 1079.03   424.5 1081.11   445.9 1089.33
   460.8 1097.56   469.7 1103.66   492.6 1114.97   501.7 1118.17   518.9 1122.03
#Mann= 7 ,-1,0
       0      .1       0     150     .06       0  199.72    .045       0
     225     .06       0     250      .1       0  384.41     .06       0
  474.41      .1       0
Bank Sta=199.72,225
XS Rating Curve= 0 ,0
Exp/Cntr(USF)=0,0
Exp/Cntr=0.3,0.1

Type RM Length L Ch R = 1 ,34414   ,55.6,55.8,55.5
XS GIS Cut Line= 3
1671232.58348823417431.3330131651671332.97262427417474.270535207
 1671689.7773849417497.251180807
#Sta/Elev= 30
       0 1135.89    29.9 1125.99    38.6  1121.3    47.3 1118.21    60.4 1111.94
    82.1 1100.71    86.5 1096.95    98.1 1083.97   107.2 1076.14   112.3 1072.95
   116.3 1071.89   128.4 1073.13   148.4 1071.76   156.4 1069.05  171.281059.436
   176.5 1057.83   180.5 1057.69   188.5  1059.3   196.5  1062.8   200.5 1063.23
   264.9 1062.94   296.7 1063.86   340.8 1067.01   360.8 1070.56   384.9 1080.49
   397.2 1087.58   408.9 1095.46     429 1107.66     453 1120.07   466.7 1125.98
#Mann= 8 ,-1,0
       0      .1       0      70     .06       0  169.19     .05       0
  171.28    .045       0   188.5     .05       0  269.19     .06       0
  369.19     .05       0  466.73      .1       0
Bank Sta=171.28,188.5
XS Rating Curve= 0 ,0
Exp/Cntr(USF)=0,0
Exp/Cntr=0.3,0.1

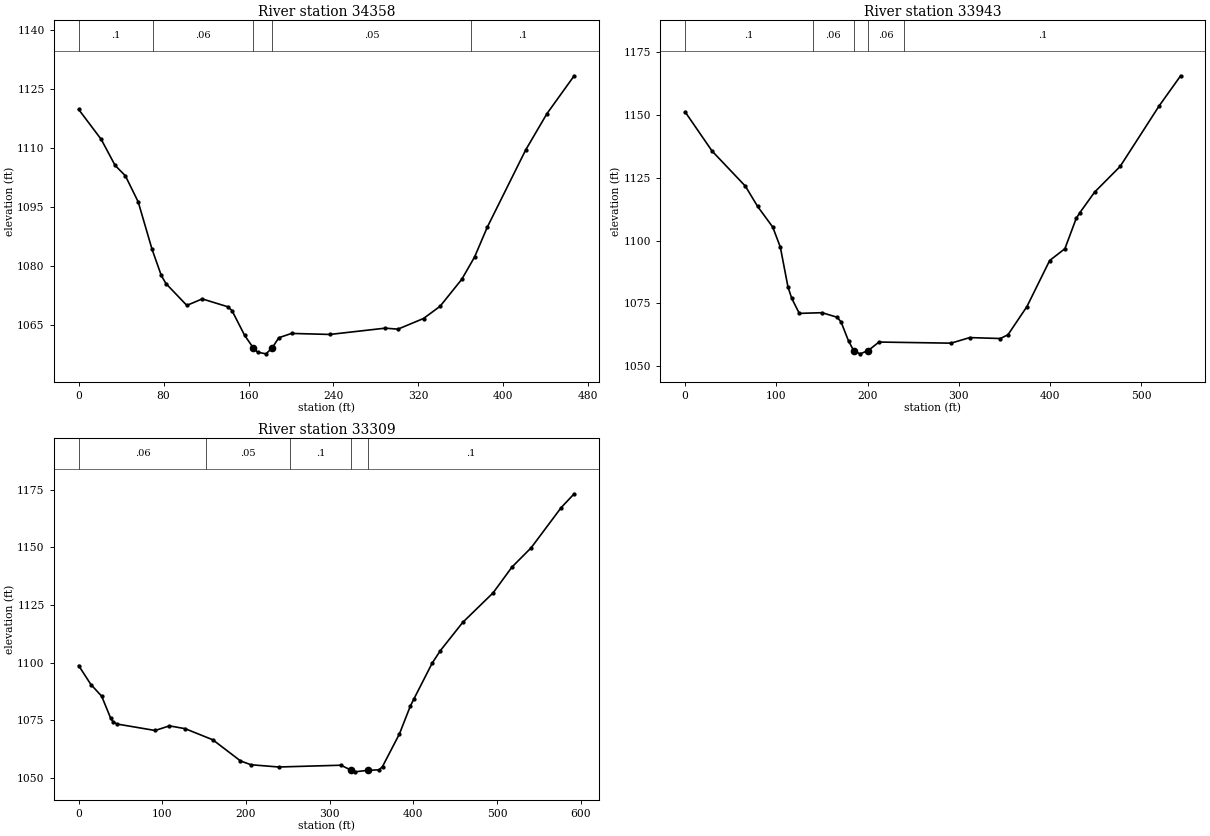
Type RM Length L Ch R = 1 ,34358   ,418.7,415.6,413.1
XS GIS Cut Line= 3
1671228.56821602417486.2739086351671328.95735206417529.211430678
1671685.76211269417552.192076278
#Sta/Elev= 30
       0 1119.86    21.3 1112.21    34.3 1105.61      44 1102.95    56.1  1096.3
    69.1 1084.26    77.8 1077.58    82.2  1075.5   101.9 1069.93   116.4 1071.58
   140.4 1069.59   144.4 1068.62   156.4 1062.27   164.5  1059.1   168.5 1058.01
   176.5 1057.59  182.391059.137   188.5 1061.69   200.5 1062.79   236.6 1062.53
   288.7 1064.13   300.7 1063.88   324.8 1066.59   340.4  1069.7   360.9  1076.6
   372.9 1082.26   384.9 1089.87     421 1109.51     441 1118.75   466.7 1128.42
#Mann= 5 ,-1,0
       0      .1       0      70     .06       0   164.5    .045       0
  182.39     .05       0  369.19      .1       0
Bank Sta=164.5,182.39
XS Rating Curve= 0 ,0
Exp/Cntr(USF)=0,0
Exp/Cntr=0.3,0.1

Type RM Length L Ch R = 1 ,33943   ,632.1,633.8,633.9
XS GIS Cut Line= 3
1671259.66634409417989.7354536381671670.01502588417872.932083541
1671786.04995276417860.636991952
#Sta/Elev= 30
       0 1151.32    29.6 1135.67    66.1 1121.68    79.5  1113.6    96.1 1105.36
   104.4 1097.38   112.8 1081.47   116.9 1076.95   125.2 1070.94   150.2 1071.22
   166.8 1069.39     171 1067.51   179.3 1059.84   184.9 1056.08   191.8 1054.81
   200.51056.055   212.6 1059.51   291.6 1059.07   312.1 1061.29   345.7 1060.92
     354 1062.43   374.8 1073.67   399.7 1092.03   416.4 1096.73   428.8 1108.82
   432.8  1111.1   448.9 1119.27     477 1129.56   519.8 1153.73   543.3  1165.7
#Mann= 5 ,-1,0
       0      .1       0     140     .06       0   184.9    .045       0
   200.5     .06       0     240      .1       0
Bank Sta=184.9,200.5
XS Rating Curve= 0 ,0
Exp/Cntr(USF)=0,0
Exp/Cntr=0.3,0.1

Type RM Length L Ch R = 1 ,33309   ,386.8,385.6,383.2
XS GIS Cut Line= 4
1671500.33088445418608.6894398461671554.12191016418509.645646489
1671881.13719339  418422.5554144 1672005.7957609 418356.81082743
#Sta/Elev= 30
       0 1098.71    14.7 1090.46    27.5 1085.44    38.3 1075.86    41.1 1074.34
    45.7 1073.36    91.4 1070.55   108.5 1072.55   127.2 1071.34   160.3 1066.52
   193.4 1057.36   205.8  1055.7     239 1054.72   313.5 1055.49   325.9 1053.27
     330 1052.62   345.3 1053.27     359  1053.5   363.1 1054.93   383.3 1069.05
   396.3  1081.1   400.4 1084.09   422.5 1099.79   432.3 1105.22     459 1117.44
   495.2 1130.21   517.8 1141.42   540.7 1149.77   576.6  1167.2   592.1 1173.18
#Mann= 5 ,-1,0
       0     .06       0  152.71     .05       0  252.71      .1       0
   325.9    .045       0   345.3      .1       0
Bank Sta=325.9,345.3
XS Rating Curve= 0 ,0
Exp/Cntr(USF)=0,0
Exp/Cntr=0.3,0.1