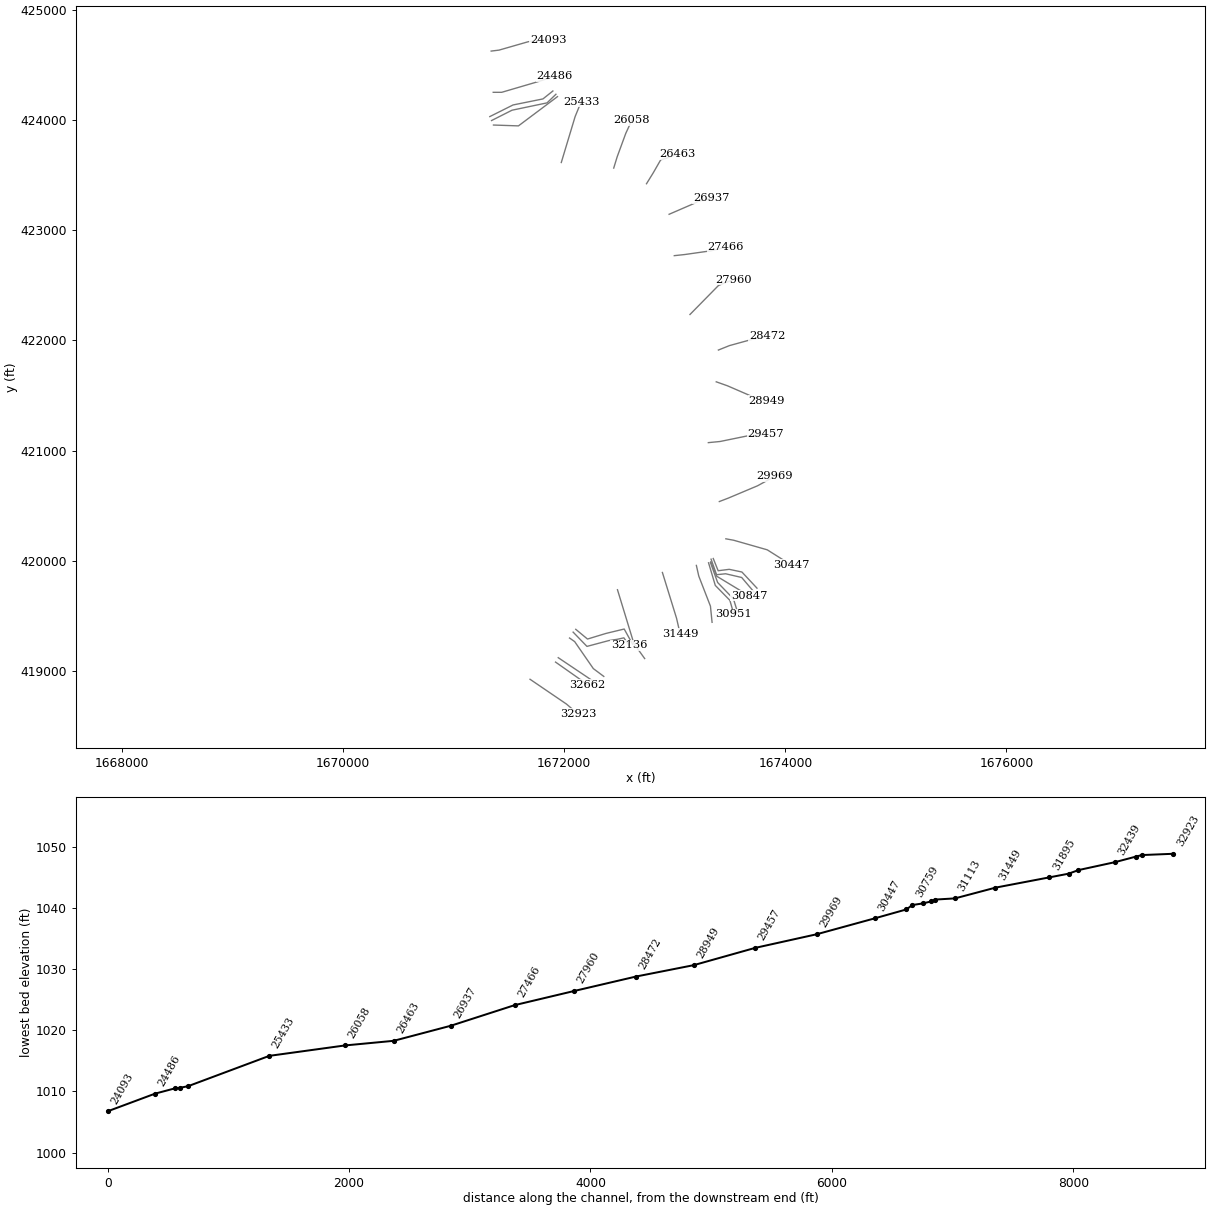
HEC-RAS study KNOBBFK.prj: KNOBBFK

--- KNOBBFK.g01 (geometry) --- (continued)

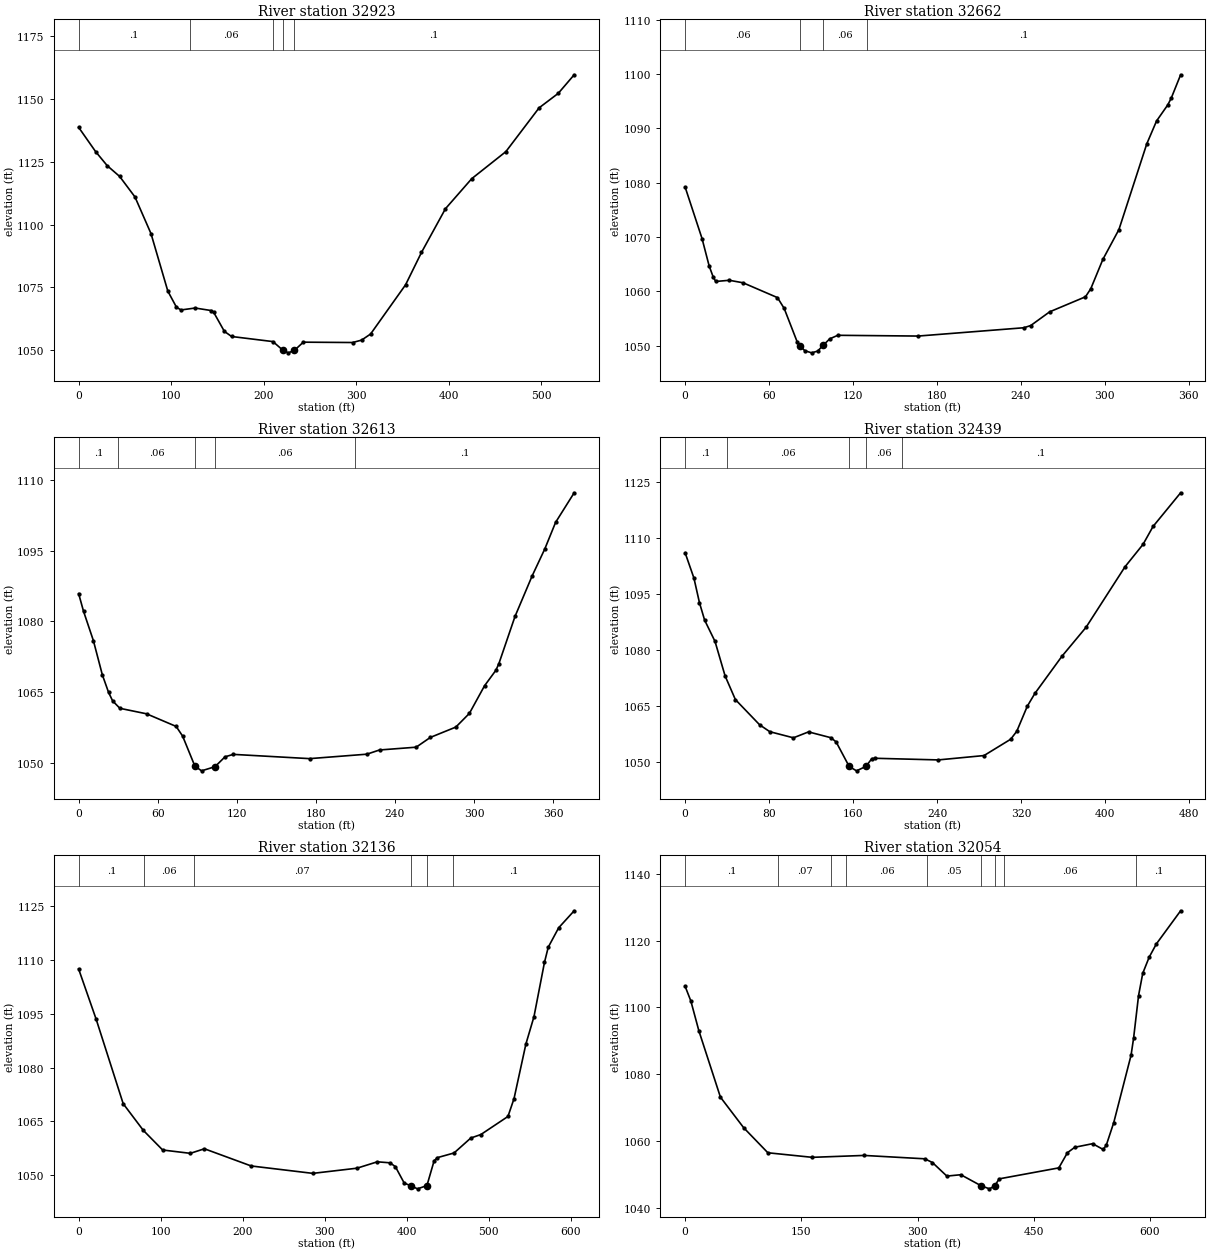
Type RM Length L Ch R = 1 ,32923   ,261.4,261.3,260.5
XS GIS Cut Line= 3
 1671691.5306418418926.8701888941672020.42434181418702.484767392
1672124.93262032418613.345353371
#Sta/Elev= 30
       0 1138.71    18.3 1129.07    30.9 1123.44    44.3 1119.16    60.9 1110.97
    78.2 1096.38    96.4 1073.45   105.7 1067.07   110.6 1065.96   125.9 1066.73
   143.1 1065.74     146 1064.98   157.5 1057.43   165.3 1055.39     210 1053.36
   220.9 1049.87   226.6 1048.88   233.1 1049.84   242.8 1053.13   296.1 1052.99
   305.8 1053.95   315.5 1056.38   353.3 1075.98   370.5 1088.88   396.4 1106.29
   424.8 1118.26   461.7 1129.04   497.6 1146.48   518.3 1152.25   535.5 1159.65
#Mann= 5 ,-1,0
       0      .1       0     120     .06       0     210      .1       0
   220.9    .045       0   233.1      .1       0
Bank Sta=220.9,233.1
XS Rating Curve= 0 ,0
Exp/Cntr(USF)=0,0
Exp/Cntr=0.3,0.1

Type RM Length L Ch R = 1 ,32662   ,48.7,48.9,49
XS GIS Cut Line= 2
1671922.25105679419082.6542400871672211.69800462418878.589872737
#Sta/Elev= 30
       0 1079.21    12.1 1069.72    17.2 1064.66    20.1 1062.62    21.9 1061.81
    31.6 1062.03    41.4 1061.57      66 1058.84    70.8 1056.85      80 1050.75
    81.9 1050.01    85.5 1049.07    90.4 1048.67    94.7 1048.99   98.641050.048
   103.3 1051.24   109.1  1051.9   166.5 1051.76   242.1 1053.29     247  1053.7
   260.5 1056.22   286.1 1058.99   289.9 1060.48   298.5 1065.86     310 1071.37
   329.9 1087.15   336.9 1091.37   344.9 1094.32   347.4 1095.58   354.1 1099.87
#Mann= 4 ,-1,0
       0     .06       0    81.9    .045       0   98.64     .06       0
     130      .1       0
Bank Sta=81.9,98.64
XS Rating Curve= 0 ,0
Exp/Cntr(USF)=0,0
Exp/Cntr=0.3,0.1

Type RM Length L Ch R = 1 ,32613   ,176.5,174,170.9
XS GIS Cut Line= 2
 1671946.6879993419122.6001473331672258.61197785418912.651315622
#Sta/Elev= 30
       0 1085.89     3.7 1082.17    11.2 1075.95      18 1068.71    22.7 1065.02
    25.8 1063.21    31.3 1061.64    51.5 1060.48      74 1057.81    78.9 1055.77
    88.21049.417    93.3 1048.42   103.51049.302   111.1 1051.39   117.4  1051.9
   175.3    1051   218.7 1051.94   228.3 1052.83   256.1 1053.42   266.9 1055.49
   286.2 1057.67   296.5 1060.57     308 1066.41   316.6 1069.68   318.9 1071.11
   331.1 1081.06   344.1 1089.63   353.7 1095.33   361.9 1100.95     376 1107.21
#Mann= 5 ,-1,0
       0      .1       0      30     .06       0    88.2    .045       0
   103.5     .06       0     210      .1       0
Bank Sta=88.2,103.5
XS Rating Curve= 0 ,0
Exp/Cntr(USF)=0,0
Exp/Cntr=0.3,0.1

Type RM Length L Ch R = 1 ,32439   ,291.8,302.9,308.2
XS GIS Cut Line= 4
 1672048.8665281419300.9191973171672094.97312156419268.644581895
1672264.03063091419023.511193337 1672358.5491475418952.814416699
#Sta/Elev= 30
       0 1106.02     8.4 1099.23    13.7 1092.59    18.6 1087.94    28.5 1082.23
    38.1 1072.98    47.9 1066.63      71 1059.86    80.7 1058.01   103.2 1056.37
   117.6 1057.96     139 1056.39   143.9 1055.26   156.31048.694   163.3 1047.51
   172.2 1048.69   177.9 1050.77   180.8 1050.88   241.2 1050.44   284.8 1051.61
   310.2 1055.99     316 1058.13     326 1064.84   333.2 1068.26     359 1078.24
     382 1086.02   419.1 1102.25   436.3 1108.27   445.8 1113.06   472.1  1122.1
#Mann= 5 ,-1,0
       0      .1       0      40     .06       0   156.3    .045       0
   172.2     .06       0  206.28      .1       0
Bank Sta=156.3,172.2
XS Rating Curve= 0 ,0
Exp/Cntr(USF)=0,0
Exp/Cntr=0.3,0.1

Type RM Length L Ch R = 1 ,32136   ,81.1,82,81.7
XS GIS Cut Line= 6
1672081.26231242419354.418923315 1672206.2563848419225.039350319
1672405.37911735419278.1870141981672480.44414191419289.298964509
1672540.25981069419302.6528499891672585.98733718419236.125198959
#Sta/Elev= 30
       0 1107.45    21.4 1093.43    54.3 1069.93    78.9 1062.48   102.4 1057.03
   136.1  1056.1   153.3 1057.37   210.3 1052.58   285.4 1050.52   339.2 1051.96
     364 1053.74   379.5 1053.46     386 1052.39   396.8 1047.81   404.6 1047.09
     413 1046.21  424.451047.121   433.2 1054.01   437.3 1054.91   457.5  1056.2
   477.9 1060.36   490.2 1061.34   523.2 1066.37   530.6 1071.34   545.1 1086.58
   554.9 1094.16   567.7 1109.29   572.3 1113.52     585 1118.93   603.9 1123.67
#Mann= 6 ,-1,0
       0      .1       0      80     .06       0     140     .07       0
   404.6    .045       0  424.45     .07       0  455.99      .1       0
Bank Sta=404.6,424.45
XS Rating Curve= 0 ,0
Exp/Cntr(USF)=0,0
Exp/Cntr=0.3,0.1

Type RM Length L Ch R = 1 ,32054   ,174.2,159,150.1
XS GIS Cut Line= 5
1672105.02879401419379.9163878271672211.15489083419291.659032406
1672377.66621317419342.4829768661672543.03238282 419382.58548768
1672619.06383247419244.966355694
#Sta/Elev= 30
       0 1106.32     7.4 1101.93    17.8 1092.96    45.6 1073.09    75.6 1063.93
   106.8 1056.43   164.1 1055.06     231 1055.63   309.3 1054.62   319.2  1053.5
   337.8 1049.44   355.8 1049.85   382.1 1046.53   392.8 1045.62   399.6 1046.52
   405.3 1048.61   482.3  1051.9   493.4 1056.44   502.9 1058.08   525.9 1059.15
   539.5 1057.42   543.5 1058.66   553.2 1065.49   575.5 1085.63   578.8 1090.79
   585.2 1103.55   590.6  1110.2   598.9 1115.04   608.2 1119.02   639.5 1128.94
#Mann= 9 ,-1,0
       0      .1       0     120     .07       0  188.03      .1       0
  208.03     .06       0  312.12     .05       0   382.1    .045       0
   399.6     .05       0  412.12     .06       0  582.28      .1       0
Bank Sta=382.1,399.6
XS Rating Curve= 0 ,0
Exp/Cntr(USF)=0,0
Exp/Cntr=0.3,0.1

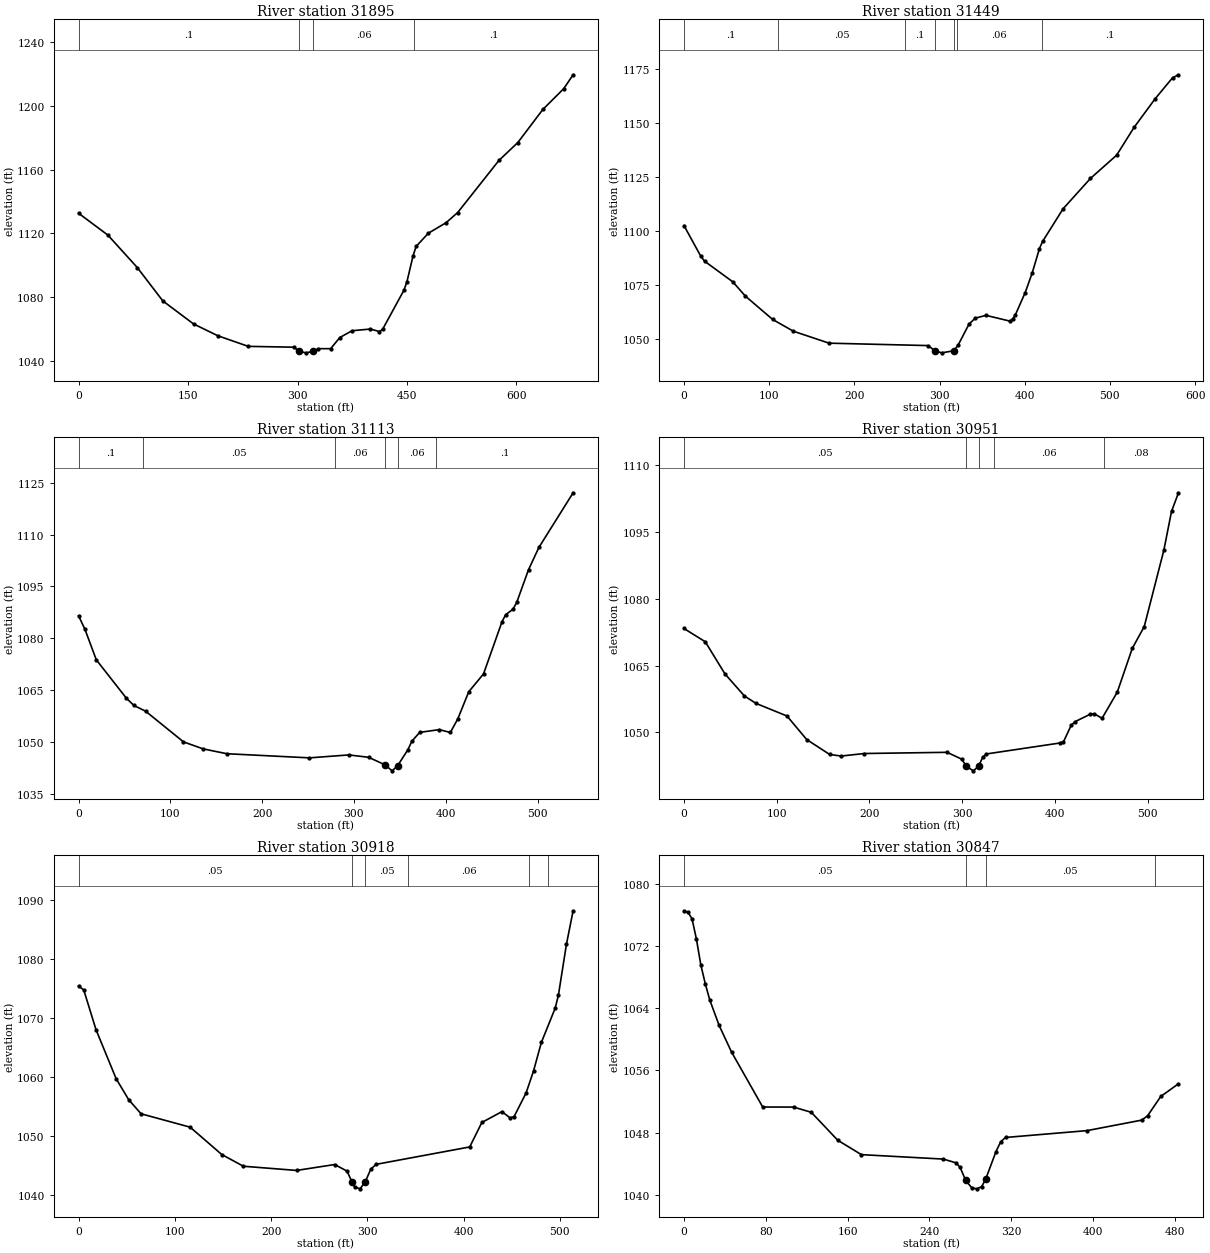
Type RM Length L Ch R = 1 ,31895   ,445.9,446.3,445.8
XS GIS Cut Line= 3
1672482.23575378419738.9581349551672630.98181305419250.555719863
1672728.19380454419114.693177535
#Sta/Elev= 30
       0  1132.6    40.2 1118.86    80.4 1098.55   115.4  1077.6   157.5 1063.16
   190.7 1055.76   232.5 1049.08   295.2 1048.56   302.2 1045.87     312 1045.02
   321.71046.054   328.7 1047.65   345.4 1047.62   357.9 1054.63   374.7 1058.89
   399.8 1059.95   412.3 1058.36   416.5 1059.72   445.8 1084.31   449.9 1089.59
   458.3 1105.93   462.5  1111.8   479.2 1120.05   503.5 1126.65   519.4 1133.02
   575.9 1165.71   601.9 1176.98   636.2 1197.74   664.8 1210.79   677.6 1219.47
#Mann= 4 ,-1,0
       0      .1       0   302.2    .045       0   321.7     .06       0
     460      .1       0
Bank Sta=302.2,321.7
XS Rating Curve= 0 ,0
Exp/Cntr(USF)=0,0
Exp/Cntr=0.3,0.1

Type RM Length L Ch R = 1 ,31449   ,335,335.9,335.1
XS GIS Cut Line= 3
1672888.60750226419895.3439928521673016.68137298419479.530825915
1673049.12675356419337.795742318
#Sta/Elev= 30
       0 1102.48    19.7 1088.27    24.2 1085.91    57.3 1076.34    72.2 1069.65
   104.2 1058.83   128.5 1053.37   170.4 1047.83   286.6 1046.71  294.731044.258
   302.6 1043.34   316.8 1044.31   321.8  1046.9   334.6 1056.67     342 1059.46
   354.5 1060.75   382.6 1058.08   385.8    1059     389 1060.97   400.6 1071.35
   408.9 1080.57   417.3 1091.77     421 1095.09   445.1 1110.27   477.2 1124.36
   507.9 1135.15   528.4 1148.07   553.1 1161.34   573.6 1171.13   580.5 1172.49
#Mann= 7 ,-1,0
       0      .1       0     110     .05       0     260      .1       0
  294.73    .045       0   316.8      .1       0     320     .06       0
     420      .1       0
Bank Sta=294.73,316.8
XS Rating Curve= 0 ,0
Exp/Cntr(USF)=0,0
Exp/Cntr=0.3,0.1

Type RM Length L Ch R = 1 ,31113   ,158.4,162,163.9
XS GIS Cut Line= 4
1673195.73767641419959.390201377 1673217.5527354419862.382767615
1673323.03746128419589.8432032121673337.73227153419443.494910924
#Sta/Elev= 30
       0 1086.49       7 1082.53    19.3 1073.74    52.1 1062.61    60.3 1060.51
      73 1058.86   114.3 1049.97   135.7 1047.94   161.5 1046.54   251.5 1045.34
   294.4 1046.19   315.9 1045.51   333.71043.346   341.6 1041.58   347.61043.079
   358.8  1047.7     363 1050.11   371.6 1052.72     393 1053.52     405 1052.69
   413.1 1056.59   425.1 1064.49   441.2 1069.66   461.3 1084.77   465.3  1086.8
   473.4 1088.42   477.4  1090.4   490.2 1099.84   501.5 1106.29   538.8 1122.13
#Mann= 6 ,-1,0
       0      .1       0      70     .05       0  279.43     .06       0
   333.7    .045       0   347.6     .06       0  389.43      .1       0
Bank Sta=333.7,347.6
XS Rating Curve= 0 ,0
Exp/Cntr(USF)=0,0
Exp/Cntr=0.3,0.1

Type RM Length L Ch R = 1 ,30951   ,33.3,33.2,33.2
XS GIS Cut Line= 4
1673305.93402737419983.0009870871673366.84560436419777.997507538
1673498.49320624419643.0750896881673534.51618188419517.322156546
#Sta/Elev= 30
       0 1073.35      23 1070.37    44.3 1063.13    65.2  1058.2    77.7 1056.53
   111.1  1053.7   132.4 1048.41     157 1045.08   169.5 1044.71   194.5 1045.28
   283.7 1045.55   299.7 1043.99  304.19 1042.46     312 1041.39   317.6 1042.42
   322.1 1044.42   326.1 1045.18   405.7 1047.65   409.2  1047.9   417.5  1051.6
   421.7 1052.43   438.3 1054.13   442.5 1054.19   450.8 1053.18   467.2 1059.06
   483.4 1068.89   496.3 1073.79   517.4  1090.9   525.7 1099.64   533.2 1103.82
#Mann= 5 ,-1,0
       0     .05       0  304.19    .045       0   317.6     .05       0
  333.86     .06       0  452.37     .08       0
Bank Sta=304.19,317.6
XS Rating Curve= 0 ,0
Exp/Cntr(USF)=0,0
Exp/Cntr=0.3,0.1

Type RM Length L Ch R = 1 ,30918   ,68.4,70.7,73
XS GIS Cut Line= 4
1673322.91320694419985.5709764081673388.13190814419804.523516873
1673530.74587592419656.4263661441673564.97197037 419545.94692311
#Sta/Elev= 30
       0 1075.49     5.4 1074.79    18.1 1068.07      39 1059.76    52.1 1056.19
    64.9 1053.81   115.9 1051.54   148.7 1046.91   171.2 1044.92   226.4 1044.21
     266 1045.21   278.9 1044.09  283.781042.328   286.8  1041.4   292.4 1041.09
   297.9 1042.33   303.5 1044.41     309 1045.24   406.3 1048.19   418.9 1052.34
   439.8 1054.18   448.2 1053.11   452.4 1053.34   464.9 1057.36   472.6 1061.08
   480.7  1065.9     495 1071.68   498.4 1073.89   506.8 1082.58   513.7 1088.22
#Mann= 6 ,-1,0
       0     .05       0  283.78    .045       0   297.9     .05       0
  342.44     .06       0  468.04     .08       0  488.04      .1       0
Bank Sta=283.78,297.9
XS Rating Curve= 0 ,0
Exp/Cntr(USF)=0,0
Exp/Cntr=0.3,0.1

Type RM Length L Ch R = 1 ,30847   ,84.4,87.8,90
XS GIS Cut Line= 3
1673326.57426252 419991.859611351673379.62628119419861.587432173
1673672.59131762419683.568436194
#Sta/Elev= 30
       0 1076.54     4.1 1076.33     7.9 1075.51    12.2  1072.9    16.5 1069.58
    20.9 1067.13    25.2 1065.08    34.4 1061.79    46.5 1058.37      77 1051.29
   107.2 1051.28   124.5 1050.61   150.4 1047.01   173.5 1045.16   253.6 1044.59
   265.9 1044.11   269.9 1043.55   275.41041.868   281.3  1040.9   286.3 1040.76
     291 1041.03  294.951041.988   305.1 1045.56   309.7 1046.82   314.4 1047.37
     394 1048.25   447.5  1049.6   453.3 1050.16   466.2 1052.65   483.5 1054.28
#Mann= 4 ,-1,0
       0     .05       0   275.4    .045       0  294.95     .05       0
  460.66     .07       0
Bank Sta=275.4,294.95
XS Rating Curve= 0 ,0
Exp/Cntr(USF)=0,0
Exp/Cntr=0.3,0.1

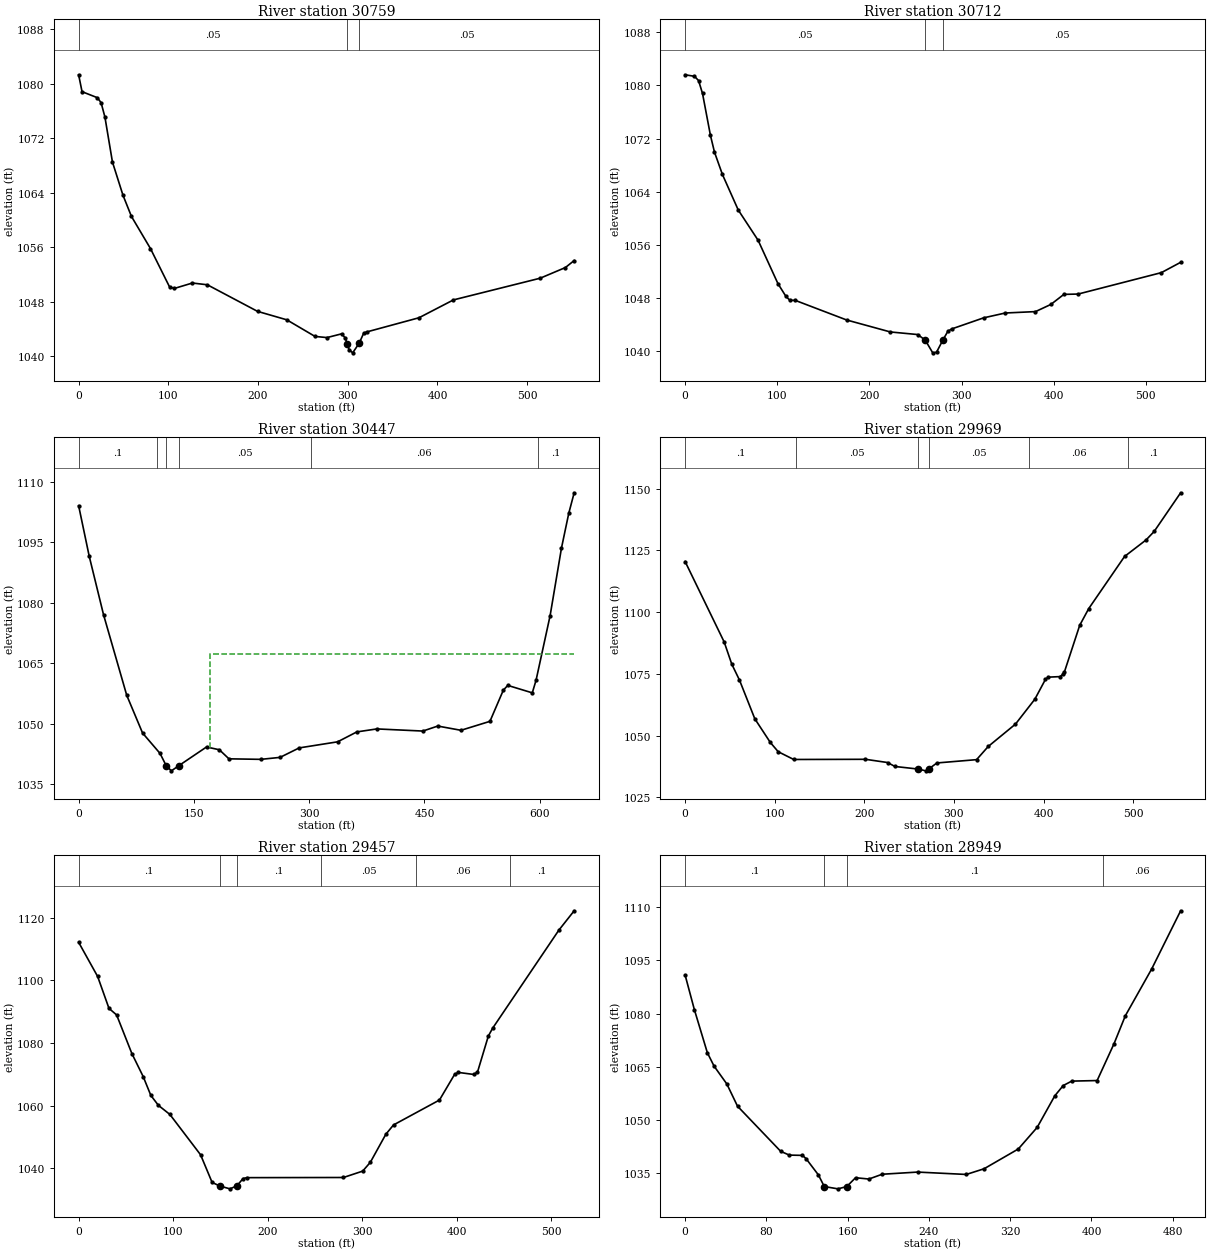
Type RM Length L Ch R = 1 ,30759   ,47.6,47.8,47.8
XS GIS Cut Line= 5
1673328.75390812 420016.13759555 1673378.2758048419875.256337756
1673460.53318326419883.6550693961673605.42699312419849.993094347
1673716.58775417419719.216504648
#Sta/Elev= 30
       0 1081.31     3.8 1078.83    20.8 1077.95      25 1077.23    29.3 1075.11
    37.7  1068.5    49.4 1063.64    58.9 1060.51    80.1 1055.79   101.3 1050.18
   106.6 1049.94   126.8 1050.74   143.5 1050.48   199.4 1046.58     232 1045.34
   263.5  1042.9   276.8 1042.73   293.2 1043.28   297.3 1042.66299.29691041.824
   301.4 1040.98   305.5 1040.49  312.771041.908   317.8 1043.39   320.9 1043.55
   379.4 1045.64   417.8 1048.26   514.6 1051.45   542.6 1053.01   552.4 1054.04
#Mann= 3 ,-1,0
       0     .05       0299.2969    .045       0  312.77     .05       0
Bank Sta=299.2969,312.77
XS Rating Curve= 0 ,0
Exp/Cntr(USF)=0,0
Exp/Cntr=0.3,0.1

Type RM Length L Ch R = 1 ,30712   ,265,264.3,264
XS GIS Cut Line= 5
1673348.39190163420022.1143761831673392.79084348419911.117021558
1673492.77217849419923.9523139111673607.56989131419899.609944796
1673743.89696852419753.212662562
#Sta/Elev= 30
       0 1081.59    10.2 1081.36    14.6 1080.72    18.9 1078.78    27.5 1072.48
    31.9 1069.95    40.5  1066.6    57.7 1061.25    79.2 1056.71   100.8 1050.17
   109.4 1048.27   113.7 1047.68   119.5 1047.67   175.3 1044.72   222.7 1042.92
   252.4 1042.53   260.6 1041.69   268.7 1039.78   272.8 1039.87     280 1041.77
   285.1 1043.02   289.2 1043.37   323.9 1045.04   347.4 1045.77   380.2 1045.98
   396.9 1047.06     411 1048.57   426.5 1048.62   516.8 1051.84   537.7 1053.39
#Mann= 3 ,-1,0
       0     .05       0   260.6    .045       0     280     .05       0
Bank Sta=260.6,280
XS Rating Curve= 0 ,0
Exp/Cntr(USF)=0,0
Exp/Cntr=0.3,0.1

Type RM Length L Ch R = 1 ,30447   ,472.8,478.3,481.3
XS GIS Cut Line= 4
1673462.51389342420200.7174290981673533.21067006420187.653894285
1673836.74574367420100.8198099361674054.01505363419963.233719098
#Sta/Elev= 30
       0  1104.1    13.8 1091.53    32.4 1077.05    62.6 1057.05    83.2 1047.69
   105.9 1042.64   113.91039.607   120.7 1038.31   130.61039.621   166.4 1044.23
   183.1 1043.54   195.6 1041.29   237.2 1041.16   262.1 1041.65     287    1044
     337 1045.51     362 1047.97   388.1 1048.71   447.9 1048.18   467.3 1049.42
   497.5 1048.37   535.2 1050.59   552.6 1058.32   558.4 1059.51   590.3 1057.66
   595.2 1060.78   613.5 1076.82   628.3 1093.61   637.8 1102.24   644.8  1107.3
#Mann= 6 ,-1,0
       0      .1       0  101.89     .05       0   113.9    .045       0
   130.6     .05       0  301.89     .06       0  597.61      .1       0
#XS Ineff= 2 , 0
                           171.1          1067.4
Permanent Ineff=
       F       F
Bank Sta=113.9,130.6
XS Rating Curve= 0 ,0
Exp/Cntr(USF)=0,0
Exp/Cntr=0.3,0.1

Type RM Length L Ch R = 1 ,29969   ,511.9,511.7,509.1
XS GIS Cut Line= 4
1673403.41616541 420538.697471311673481.79737429420568.666757058
1673749.21561635420681.6279110331673905.97803411420767.693552157
#Sta/Elev= 30
       0 1120.46    43.6 1087.89    52.1  1078.9    60.7 1072.45    77.8 1056.79
    95.1 1047.21   103.9 1043.46   121.2 1040.32   201.3 1040.39     226 1039.08
   234.1 1037.49   260.1 1036.44   268.6 1035.72   271.8 1036.44     281 1038.91
   325.3 1040.25   338.3 1045.59   368.7 1054.64   390.3 1064.71   402.1 1072.72
   405.2 1073.64   418.6 1073.87   421.8 1074.88   423.2 1075.64   440.4 1094.66
   450.5 1101.43   490.4 1122.49   514.4 1129.18   523.5 1132.64     553 1148.28
#Mann= 6 ,-1,0
       0      .1       0  123.92     .05       0   260.1    .045       0
   271.8     .05       0  384.21     .06       0  494.21      .1       0
Bank Sta=260.1,271.8
XS Rating Curve= 0 ,0
Exp/Cntr(USF)=0,0
Exp/Cntr=0.3,0.1

Type RM Length L Ch R = 1 ,29457   ,515,508,503.1
XS GIS Cut Line= 4
1673304.11922034421072.8240852211673410.37309827421083.259733946
1673655.13649565421133.5405868951673822.10687525421147.771016975
#Sta/Elev= 30
       0 1112.16    20.1 1101.26    32.1 1091.08    40.2 1088.97    56.3 1076.67
    68.3  1069.3    76.4 1063.29    84.4 1060.12    96.5 1057.23     129 1044.35
   141.2 1035.53   149.4 1034.37   160.1 1033.48   167.41034.444   173.9 1036.75
     178 1037.05   280.1  1037.1   300.5 1039.14   308.6 1041.96     325 1050.91
   333.1 1053.87   381.7 1061.82   397.8 1070.05   401.8 1070.63   417.8 1069.99
   421.9  1070.7   433.4 1082.24   437.9 1084.72     508 1116.04   524.2 1122.22
#Mann= 6 ,-1,0
       0      .1       0   149.4    .045       0   167.4      .1       0
  256.77     .05       0  356.64     .06       0  456.64      .1       0
Bank Sta=149.4,167.4
XS Rating Curve= 0 ,0
Exp/Cntr(USF)=0,0
Exp/Cntr=0.3,0.1

Type RM Length L Ch R = 1 ,28949   ,467,477.5,481.5
XS GIS Cut Line= 4
1673375.51273547421624.4067542041673477.40964221421588.098660996
1673709.31294722421487.3729830631673831.12074379421452.236118668
#Sta/Elev= 30
       0 1090.87     9.1 1081.14    21.9 1068.99    28.5 1065.22    41.1 1060.18
    51.6 1053.93    94.1 1041.22   102.6 1040.16   115.5 1040.08     119 1039.19
   131.2 1034.59  137.021031.308   150.4 1030.66   159.1 1031.29   167.8 1033.79
   180.9 1033.42     194 1034.77   228.9 1035.38   276.8 1034.71   294.3 1036.31
     328 1041.88   346.6 1047.97   363.9 1056.84   372.2 1059.74   380.6 1060.99
   405.6 1061.15   422.2  1071.5   433.4 1079.41   459.3 1092.57   487.8 1108.95
#Mann= 4 ,-1,0
       0      .1       0  137.02    .045       0   159.1      .1       0
  411.01     .06       0
Bank Sta=137.02,159.1
XS Rating Curve= 0 ,0
Exp/Cntr(USF)=0,0
Exp/Cntr=0.3,0.1

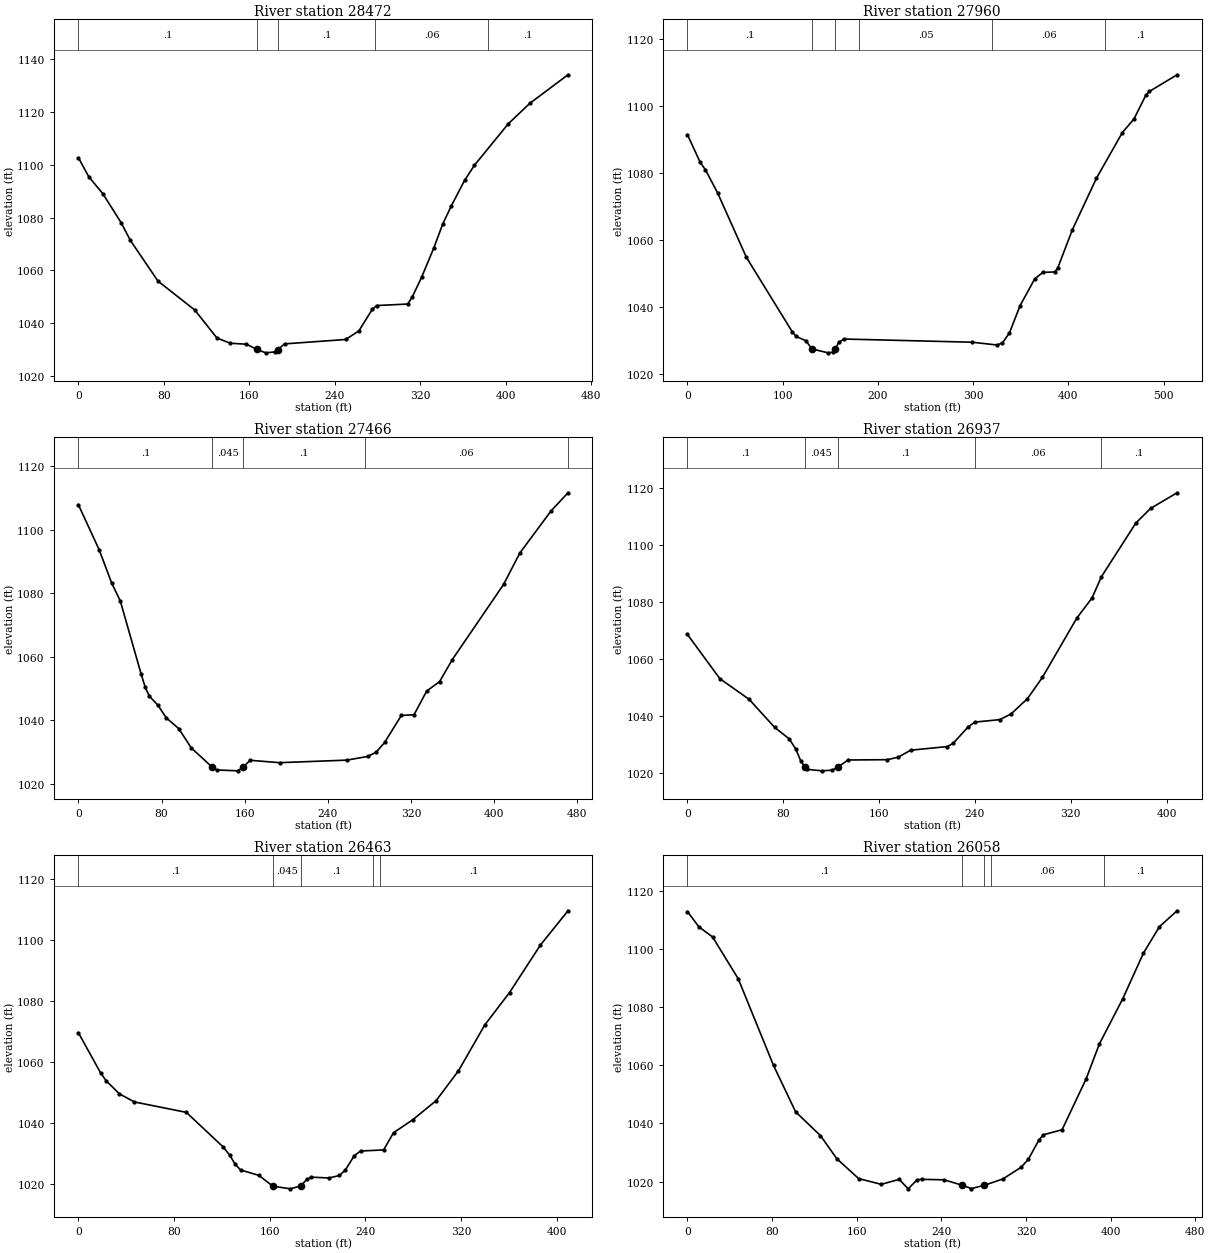
Type RM Length L Ch R = 1 ,28472   ,501.6,511.8,512.4
XS GIS Cut Line= 4
1673394.98755363421912.5429976611673495.19268542421952.885323448
1673693.00021831422007.5426680631673834.84904124422037.474071066
#Sta/Elev= 30
       0 1102.68     9.8 1095.43    22.8 1089.09      40  1078.1    48.6 1071.42
    74.5 1055.96     109 1044.99   129.7 1034.42   142.2 1032.43   157.3 1032.07
   167.1 1030.08   175.4  1028.8   183.7 1029.15   186.5 1030.02     193 1032.19
   250.1 1033.85   262.5 1037.09     275 1045.21   279.1  1046.7   308.2 1047.27
   312.3 1049.81   321.2  1057.4   332.8 1068.65     341 1077.59   349.1 1084.47
   361.4 1094.05   370.7 1099.82   402.3 1115.48   422.7 1123.31   458.2 1134.04
#Mann= 5 ,-1,0
       0      .1       0   167.1    .045       0   186.5      .1       0
  278.02     .06       0  383.24      .1       0
Bank Sta=167.1,186.5
XS Rating Curve= 0 ,0
Exp/Cntr(USF)=0,0
Exp/Cntr=0.3,0.1

Type RM Length L Ch R = 1 ,27960   ,499.3,494.2,482.4
XS GIS Cut Line= 3
1673137.95536182422234.9575091061673396.21131512422498.483992069
 1673531.1368744422552.243394594
#Sta/Elev= 30
       0 1091.55    13.4 1083.28      19 1081.02    31.7 1074.17      62  1054.9
   110.1 1032.72   114.2 1031.34   124.3 1030.06     131 1027.58   147.8 1026.44
   152.6 1026.63   155.4 1027.65     159 1029.61   164.6 1030.56     299 1029.61
   325.1 1028.78   330.8 1029.41   338.2 1032.38   349.4 1040.56   364.7 1048.49
   373.2 1050.44   385.9 1050.57     389 1051.83   404.3 1063.19   429.5 1078.51
   456.7 1092.13     469 1096.24   481.3 1103.24   485.1 1104.42   514.2 1109.39
#Mann= 6 ,-1,0
       0      .1       0     131    .045       0   155.4      .1       0
     180     .05       0     320     .06       0  438.97      .1       0
Bank Sta=131,155.4
XS Rating Curve= 0 ,0
Exp/Cntr(USF)=0,0
Exp/Cntr=0.3,0.1

Type RM Length L Ch R = 1 ,27466   ,519.8,528.8,524.8
XS GIS Cut Line= 4
1672996.08584708422768.4729833511673090.86051142422778.718893008
1673323.95495613422812.0180993951673460.56708489422843.609654173
#Sta/Elev= 30
       0  1107.9    20.1 1093.65    32.2 1083.11    40.3 1077.65    60.4 1054.59
    64.4 1050.37    68.4 1047.58    76.5  1044.8    84.5 1040.83    96.6 1037.41
   108.7 1031.31   128.9 1025.25     133 1024.41   153.2 1024.12   158.1  1025.2
   165.3 1027.44   193.6 1026.69   258.2 1027.49   278.4 1028.65   286.5    1030
   294.6 1033.04   310.7 1041.55   322.9 1041.78   335.1 1049.25   347.4 1052.17
   359.7 1059.12     409 1082.77   424.7 1092.68   454.7 1105.92     471 1111.63
#Mann= 5 ,-1,0
       0      .1       0   128.9    .045       0   158.1      .1       0
  275.33     .06       0  470.79      .1       0
Bank Sta=128.9,158.1
XS Rating Curve= 0 ,0
Exp/Cntr(USF)=0,0
Exp/Cntr=0.3,0.1

Type RM Length L Ch R = 1 ,26937   ,463.5,473.9,478.8
XS GIS Cut Line= 4
1672949.21572813423143.7260062891673177.44336576423242.855182227
1673209.71798118423260.5293763861673329.59512417423288.193332462
#Sta/Elev= 30
       0 1068.56    27.1 1053.04    51.5 1045.81    72.9 1035.94    84.9 1031.98
    90.4 1028.41    94.7 1024.16    98.21021.998   100.1 1021.27   112.2 1020.75
   120.9 1020.99   125.3 1021.95     134 1024.55     167 1024.66   176.1 1025.56
   186.3 1027.98   216.8 1029.25   221.7 1030.33   234.3 1036.13     240 1037.83
   260.7 1038.69   270.1 1040.68   283.8 1046.02   296.3 1053.49     325 1074.26
   337.7 1081.31   345.6 1088.79   374.3 1107.58   386.6  1112.7   408.7 1118.18
#Mann= 5 ,-1,0
       0      .1       0    98.2    .045       0   125.3      .1       0
     240     .06       0  345.62      .1       0
Bank Sta=98.2,125.3
XS Rating Curve= 0 ,0
Exp/Cntr(USF)=0,0
Exp/Cntr=0.3,0.1

Type RM Length L Ch R = 1 ,26463   ,403.7,405,405
XS GIS Cut Line= 5
1672744.71102031423420.6180143661672805.84916436 423519.70397196
  1672873.311944423637.7638363281672926.01724059423652.521319374
1673021.94088039423688.360921057
#Sta/Elev= 30
       0 1069.65    18.7 1056.35    23.4 1053.73    34.4  1049.5    46.9 1046.85
    90.3 1043.43     121 1032.09   126.6 1029.36   131.2 1026.31   135.8 1024.47
   150.9 1022.72   162.7 1019.16   177.3 1018.28   186.1 1019.26   191.1 1021.41
   194.9 1022.12   209.7 1021.85   218.4 1022.67   223.4 1024.54   230.8 1029.19
     236 1030.71   255.3 1031.08   263.6 1036.74   279.6 1040.97   299.1 1047.23
   317.9 1057.09   339.9 1072.16   360.6 1082.82   386.5 1098.48   409.5 1109.71
#Mann= 5 ,-1,0
       0      .1       0   162.7    .045       0   186.1      .1       0
  246.43     .06       0  252.41      .1       0
Bank Sta=162.7,186.1
XS Rating Curve= 0 ,0
Exp/Cntr(USF)=0,0
Exp/Cntr=0.3,0.1

Type RM Length L Ch R = 1 ,26058   ,621.2,625.5,614.4
XS GIS Cut Line= 4
1672448.32028712423562.6775226781672479.62723329423665.136619254
1672557.42025106423877.6443751151672611.49588537 423995.28259711
#Sta/Elev= 30
       0 1112.85    10.9 1107.56    23.8  1104.1      48 1089.77    81.4 1059.94
   102.3 1043.99   125.8 1035.81   141.3 1027.85   161.9 1021.04   183.2 1019.07
   200.2 1020.78   208.7 1017.52   217.2 1020.65   221.5 1020.79   242.8 1020.62
   259.8 1018.75   268.4 1017.62   280.41018.705   298.2 1020.91   315.2 1024.86
   322.2 1027.61   332.3 1034.29   336.6 1036.11   354.2 1037.83   376.9 1055.29
   389.4 1067.28   411.5 1082.82   431.1 1098.53   446.2 1107.62   462.9  1113.1
#Mann= 5 ,-1,0
       0      .1       0   259.8    .045       0   280.4      .1       0
  287.14     .06       0  393.43      .1       0
Bank Sta=259.8,280.4
XS Rating Curve= 0 ,0
Exp/Cntr(USF)=0,0
Exp/Cntr=0.3,0.1

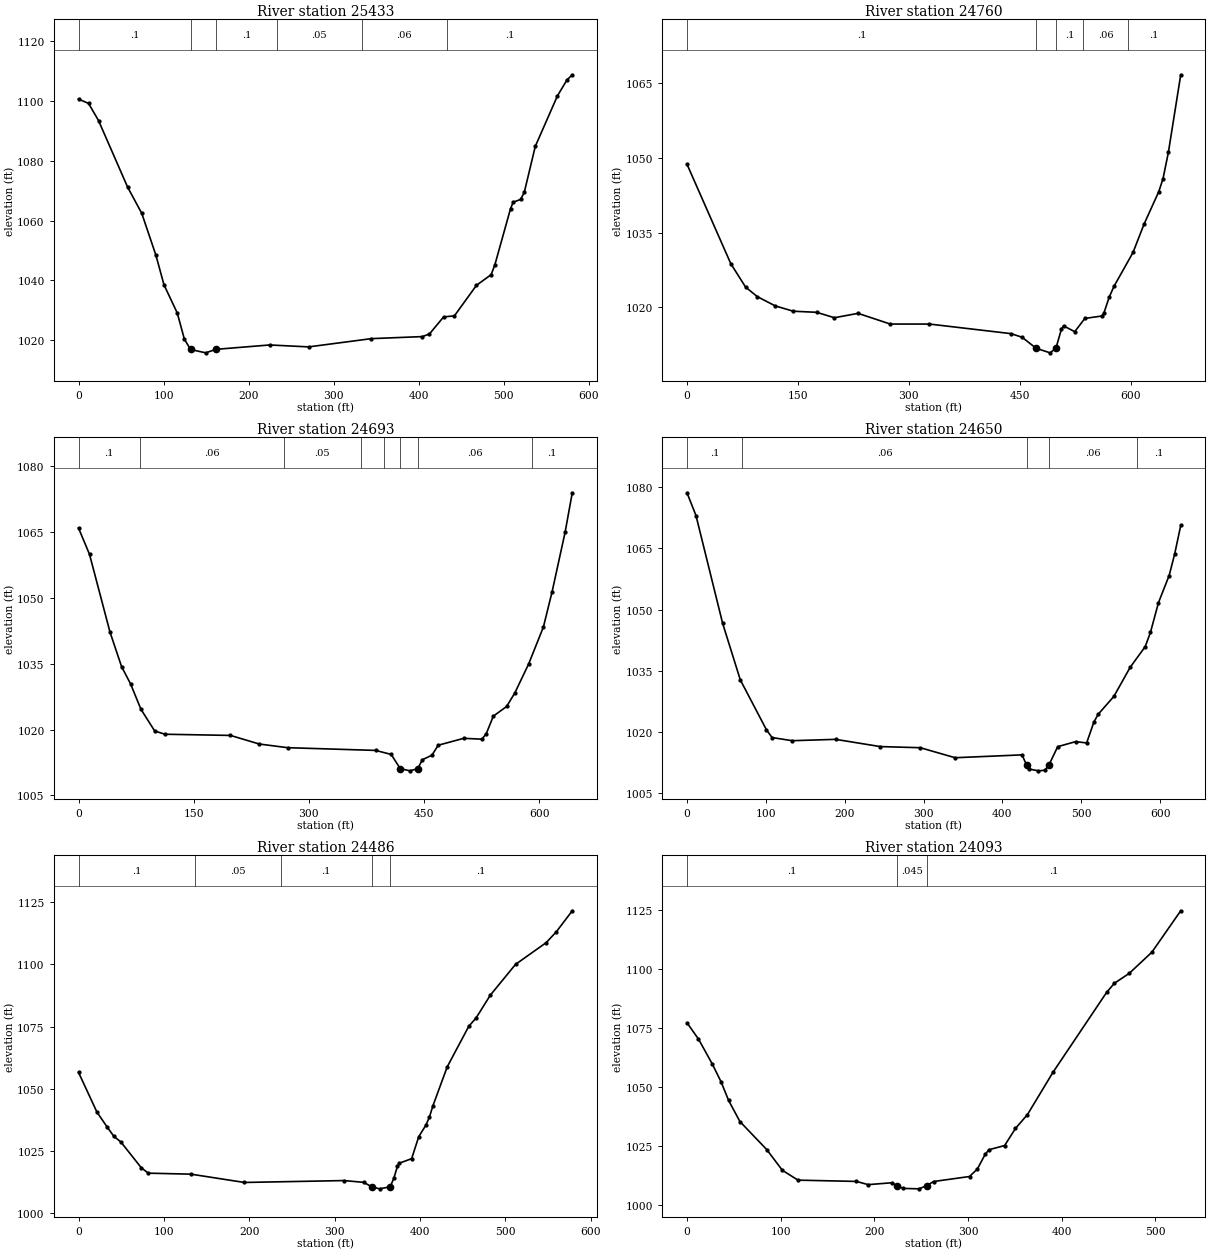
Type RM Length L Ch R = 1 ,25433   ,671.2,672.6,653.2
XS GIS Cut Line= 4
1671974.18574312423613.264089132 1672000.9628079423702.520971708
1672099.14537873424029.2011619381672154.48464593424164.871623455
#Sta/Elev= 30
       0 1100.62    11.8 1099.19    23.5 1093.46    57.7 1071.23    74.4 1062.42
    91.1 1048.37   100.5 1038.57   116.2 1029.08   124.5 1020.38   131.81016.943
   149.6 1015.82   161.6 1016.99   224.8 1018.45   270.7 1017.81   344.6 1020.57
   404.4 1021.25   412.7  1022.1   429.4 1027.81   442.2  1028.2   468.1 1038.39
   485.4 1041.96   489.8  1045.3   508.2 1064.04   511.3 1066.18     520 1067.09
   524.3 1069.42   537.3 1084.84   563.4 1101.74   574.5 1107.01   580.8 1108.76
#Mann= 6 ,-1,0
       0      .1       0   131.8    .045       0   161.6      .1       0
  233.19     .05       0  333.19     .06       0  433.19      .1       0
Bank Sta=131.8,161.6
XS Rating Curve= 0 ,0
Exp/Cntr(USF)=0,0
Exp/Cntr=0.3,0.1

Type RM Length L Ch R = 1 ,24760   ,66.1,66.6,58.2
XS GIS Cut Line= 3
1671360.89552879423953.0332802621671586.64168119423945.315463085
  1671939.731817424210.615428514
#Sta/Elev= 30
       0 1048.74    59.3 1028.74    79.3 1024.05    95.3 1022.13   119.3 1020.29
   143.7 1019.22   175.3    1019   199.3 1017.91   231.2 1018.79   274.9 1016.64
   327.8 1016.64   437.9 1014.72   452.9    1014   472.1 1011.77   490.9 1010.86
   498.8  1011.8   506.3 1015.67   509.2 1016.27   524.2 1015.11   537.9 1017.77
   560.6 1018.25   563.5 1018.79   570.8 1022.05   577.5 1024.28     603 1031.02
     618 1036.74   637.8 1043.23   643.5 1045.81   650.8 1051.12   667.5 1066.71
#Mann= 5 ,-1,0
       0      .1       0   472.1    .045       0   498.8      .1       0
  535.88     .06       0  595.88      .1       0
Bank Sta=472.1,498.8
XS Rating Curve= 0 ,0
Exp/Cntr(USF)=0,0
Exp/Cntr=0.3,0.1

Type RM Length L Ch R = 1 ,24693   ,43.4,43.7,43.9
XS GIS Cut Line= 4
1671343.58583719423993.809624279 1671528.7845076424087.581102968
1671845.26324818 424154.002567041671925.75043405424232.145465948
#Sta/Elev= 30
       0 1065.86    14.3 1059.87    40.9 1042.22      56 1034.34    67.8 1030.38
    81.3 1024.61    99.2 1019.67   112.7 1018.93   197.9 1018.66   235.5  1016.7
   272.3 1015.87   386.9 1015.25   407.2 1014.34  419.031011.108   431.7  1010.6
   441.71011.103     448 1013.14   460.3 1014.16   468.5 1016.43   501.7    1018
   525.4 1017.81     531 1019.03   540.3 1023.05   557.6 1025.25   568.4 1028.37
   586.3 1034.93   605.5 1043.34   616.8 1051.34   633.8 1064.94   643.1 1073.89
#Mann= 8 ,-1,0
       0      .1       0      80     .06       0  267.59     .05       0
  367.59      .1       0  397.59     .06       0  419.03    .045       0
   441.7     .06       0  590.96      .1       0
Bank Sta=419.03,441.7
XS Rating Curve= 0 ,0
Exp/Cntr(USF)=0,0
Exp/Cntr=0.3,0.1

Type RM Length L Ch R = 1 ,24650   ,161.2,163.2,163.2
XS GIS Cut Line= 4
1671327.71156832424029.6810438791671537.91596638424135.173957405
 1671808.2903966424189.8739866411671898.15473035424261.765453636
#Sta/Elev= 30
       0 1078.58    11.4    1073    45.2 1046.61    67.6 1032.77   100.8 1020.53
   107.9 1018.65   133.5 1017.88   188.4 1018.21     245 1016.44   295.9 1016.16
     340 1013.71   424.9 1014.41  430.81 1011.82   433.3 1010.97   445.6  1010.5
   453.7 1010.64   458.8 1011.86   470.1 1016.42   492.8 1017.65   506.8 1017.33
   515.9  1022.4   521.3 1024.32   541.3 1028.72     562 1035.85   581.1 1040.93
   587.7  1044.4   597.9 1051.69   611.4 1058.32   618.4 1063.57   626.1 1070.58
#Mann= 5 ,-1,0
       0      .1       0      70     .06       0  430.81    .045       0
   458.8     .06       0  571.04      .1       0
Bank Sta=430.81,458.8
XS Rating Curve= 0 ,0
Exp/Cntr(USF)=0,0
Exp/Cntr=0.3,0.1

Type RM Length L Ch R = 1 ,24486   ,389.3,393.2,387
XS GIS Cut Line= 4
1671358.61324192424249.780727937 1671435.2492013424249.780727937
1671769.26630728424348.1061097831671915.30841855424395.822839209
#Sta/Elev= 30
       0 1056.52    21.5 1040.58    33.5 1034.53    41.5 1030.75    49.5 1028.55
    73.5 1018.14    81.7 1015.95   131.7 1015.55   194.3 1012.21     311 1012.97
     334 1012.26   343.41010.498   352.7 1009.64   365.2 1010.47   369.5 1013.98
   373.6 1018.66   375.9 1019.96   390.3  1021.8   398.6 1030.63   406.9 1035.24
   411.1  1038.5   415.3 1043.16     432 1058.78   457.3 1075.13   465.7  1078.4
   482.5 1087.64     512 1100.02     548  1108.8   559.9 1113.19   578.5 1121.61
#Mann= 5 ,-1,0
       0      .1       0  136.64     .05       0  236.64      .1       0
   343.4    .045       0   365.2      .1       0
Bank Sta=343.4,365.2
XS Rating Curve= 0 ,0
Exp/Cntr(USF)=0,0
Exp/Cntr=0.3,0.1

Type RM Length L Ch R = 1 ,24093   ,634.1,650.1,654.6
XS GIS Cut Line= 4
1671340.00725907 424623.733787441671410.85937246424632.409556427
1671676.91628804424709.0455158071671854.76955226424727.843015278
#Sta/Elev= 30
       0 1077.04    12.2  1070.2    26.8 1059.75    36.4 1052.03    44.4 1044.19
    56.5 1035.24    85.2 1023.34   101.8 1014.61   118.5 1010.43   180.9 1009.89
   193.4 1008.53   218.4 1009.31   224.4    1008   230.9 1006.94   247.5 1006.75
   255.8 1008.04   263.2 1009.85   301.6 1011.97     310 1015.15   318.3 1021.35
   322.4 1023.31   339.1 1025.08   350.7 1032.33   363.5 1038.21   390.7 1056.08
     448 1089.93   456.2 1093.76   472.1 1097.96   496.3 1106.94   527.1 1124.47
#Mann= 3 ,-1,0
       0      .1       0   224.4    .045       0   255.8      .1       0
Bank Sta=224.4,255.8
XS Rating Curve= 0 ,0
Exp/Cntr(USF)=0,0
Exp/Cntr=0.3,0.1