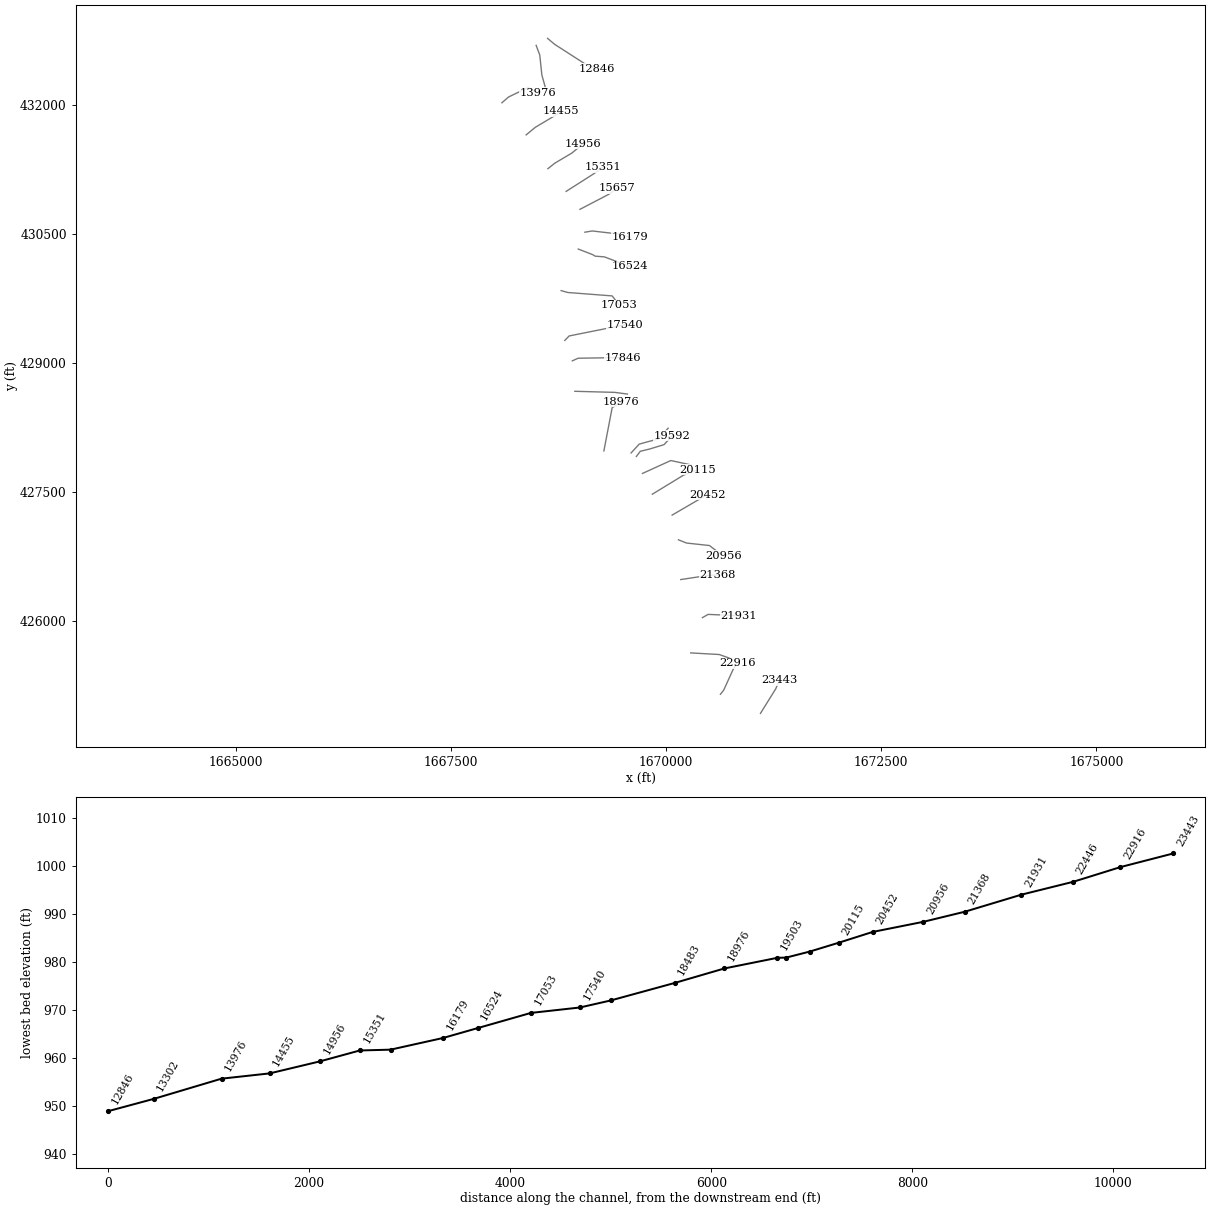
HEC-RAS study KNOBBFK.prj: KNOBBFK

--- KNOBBFK.g01 (geometry) --- (continued)

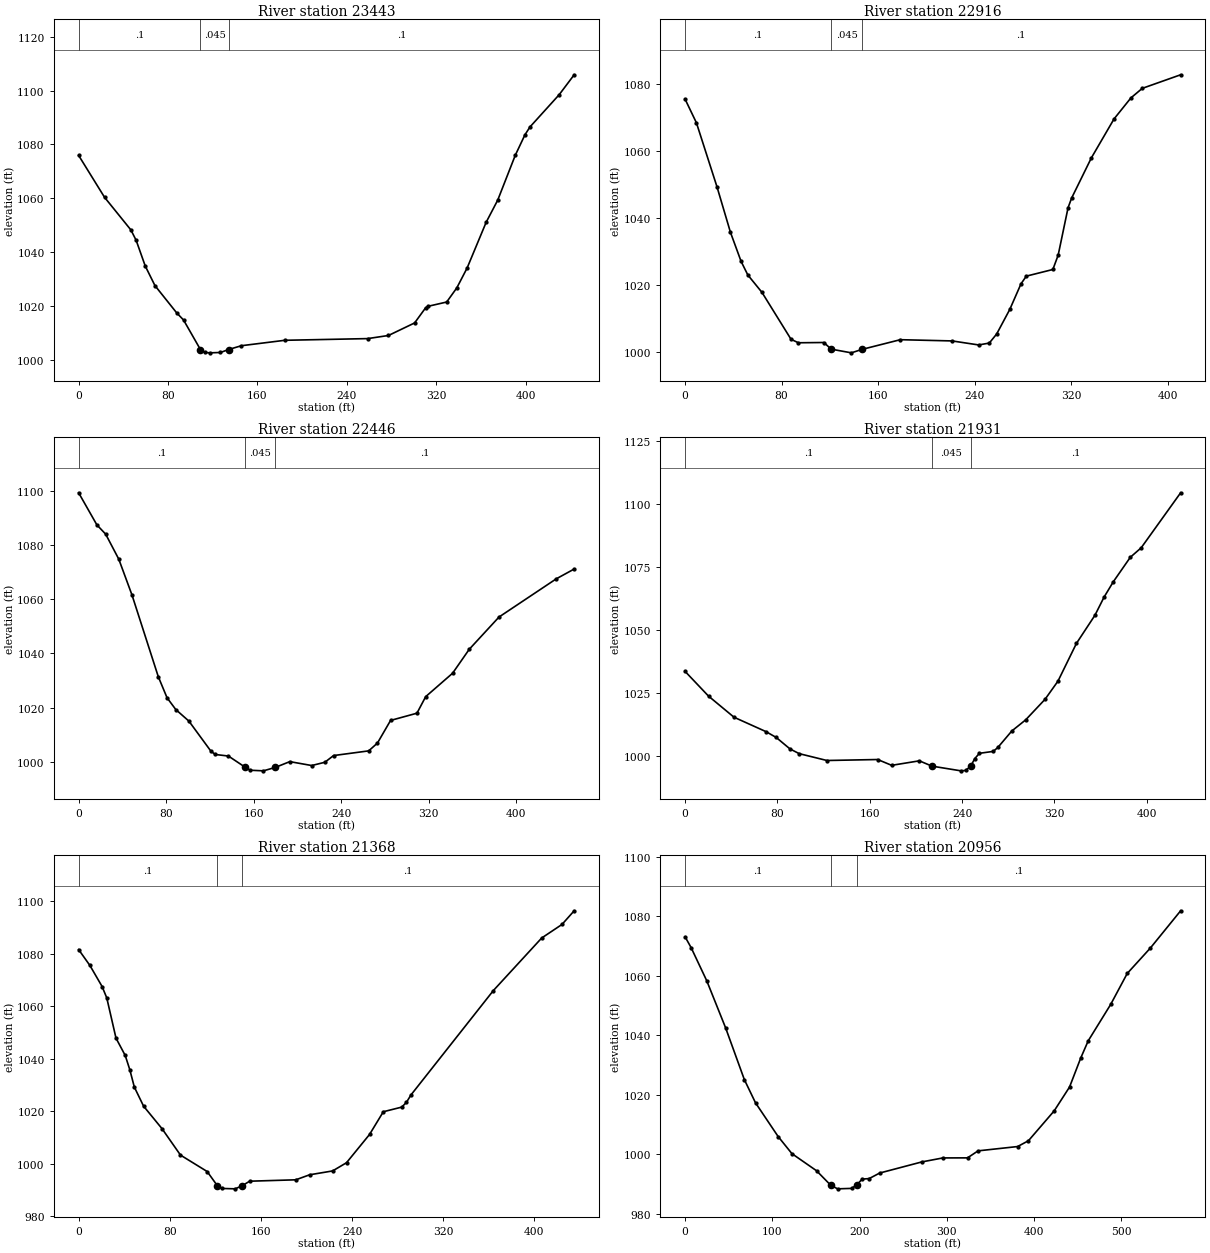
Type RM Length L Ch R = 1 ,23443   ,525.1,527.5,528.3
XS GIS Cut Line= 3
1671097.74951215424928.7965998341671274.47813965425213.169027722
1671317.85698458425312.779708677
#Sta/Elev= 30
       0 1075.94    23.2 1060.37    46.8 1048.24    51.5 1044.37    59.6 1034.87
    68.3 1027.57    87.8 1017.42    93.9 1014.79     109 1003.82   112.7 1002.73
   117.4 1002.59   126.9 1002.72   134.2 1003.82   145.7 1005.24   184.5 1007.25
   258.7 1007.88   277.3 1009.04   300.7  1013.7   310.5  1019.3   312.3 1019.84
   329.4 1021.47   338.5 1026.75   347.7 1034.12   364.7 1051.07   375.1 1059.35
   390.8    1076   399.4 1083.56   403.9  1086.5   430.1 1098.51   443.5  1105.9
#Mann= 3 ,-1,0
       0      .1       0     109    .045       0   134.2      .1       0
Bank Sta=109,134.2
XS Rating Curve= 0 ,0
Exp/Cntr(USF)=0,0
Exp/Cntr=0.3,0.1

Type RM Length L Ch R = 1 ,22916   ,483.5,469.2,451.4
XS GIS Cut Line= 4
1670632.48312953425150.9751481641670669.97102021425197.388727104
 1670777.0792793425433.0268971061670825.27799589425511.572953773
#Sta/Elev= 30
       0 1075.58     9.4  1068.5    26.4 1049.41    37.6 1035.76    46.4 1027.09
      52 1023.01    63.7 1017.82    87.8 1003.79    93.9 1002.75     115 1002.83
   121.1 1000.84   137.8  999.74   146.6 1000.77   178.4 1003.67   221.3  1003.3
   243.3  1002.1   252.1 1002.66   258.2 1005.36   269.1 1012.72   278.4 1020.38
   282.8 1022.67   304.8 1024.66   309.2 1028.95   317.4 1043.13   320.4 1046.05
   336.7 1058.02   355.5 1069.67   369.5 1075.96   378.9 1078.81   410.7 1082.87
#Mann= 3 ,-1,0
       0      .1       0   121.1    .045       0   146.6      .1       0
Bank Sta=121.1,146.6
XS Rating Curve= 0 ,0
Exp/Cntr(USF)=0,0
Exp/Cntr=0.3,0.1

Type RM Length L Ch R = 1 ,22446   ,509.6,515.2,512.5
XS GIS Cut Line= 3
  1670287.439037425631.8159787241670618.56421998425613.018479253
 1670732.7951783425572.531557317
#Sta/Elev= 30
       0 1099.33    16.7 1087.46    24.7 1084.07    36.7 1074.82    48.8 1061.56
    72.8 1031.44    80.8 1023.66    88.8 1019.31   100.8 1015.03   120.9 1003.94
   124.9 1002.72   136.9 1002.14   152.4997.9654   156.9   996.9   168.9  996.68
   179.9  997.97     193 1000.08     213  998.64     225  999.84     233 1002.32
   265.1 1004.05   273.1 1006.93   285.1 1015.29   309.2 1017.96   317.2 1024.07
   341.8 1032.72     357 1041.55   384.2 1053.46   436.6 1067.58   452.9 1071.18
#Mann= 3 ,-1,0
       0      .1       0   152.4    .045       0   179.9      .1       0
Bank Sta=152.4,179.9
XS Rating Curve= 0 ,0
Exp/Cntr(USF)=0,0
Exp/Cntr=0.3,0.1

Type RM Length L Ch R = 1 ,21931   ,550.2,562.8,563.8
XS GIS Cut Line= 4
1670423.23110826426041.7042117721670489.60074101426079.443806863
1670703.02465808426070.3342494271670842.27075031426063.827422687
#Sta/Elev= 30
       0 1033.53    20.3 1023.71    42.4 1015.31      70 1009.61    78.9 1007.29
    90.9 1002.71    98.9 1000.83   122.9  998.11   166.9   998.5     179  996.19
     203  997.98   213.9  995.87     239     994     243  994.14   247.4 995.825
     251  998.84     255 1000.97     267 1001.73     271 1003.29   283.1 1009.84
   295.1 1014.26   311.9 1022.44   323.1 1029.66   339.1 1044.66   355.1 1055.82
   363.1 1063.11   371.1  1069.2   385.8 1078.91   395.2 1082.67   429.4 1104.55
#Mann= 3 ,-1,0
       0      .1       0   213.9    .045       0   247.4      .1       0
Bank Sta=213.9,247.4
XS Rating Curve= 0 ,0
Exp/Cntr(USF)=0,0
Exp/Cntr=0.3,0.1

Type RM Length L Ch R = 1 ,21368   ,414.9,412.3,408.8
XS GIS Cut Line= 3
1670171.72535657426484.4061046291670471.55993274426530.084028343
1670602.73755982426540.625087661
#Sta/Elev= 30
       0  1081.6     9.9 1075.54    20.6 1067.52    24.7 1063.18    32.8 1047.85
    40.9 1041.25    44.9 1035.85    48.9  1029.2      57 1021.95    73.2 1013.36
    89.4  1003.3   112.8  997.05   121.8  991.61   125.8   990.6   137.4  990.45
   143.5  991.63   150.1  993.36   190.6  993.89   202.7   995.8   222.9  997.27
   235.1  1000.4   255.3 1011.16   267.4 1019.82   283.6 1021.59   287.7 1023.41
   291.7 1026.24     364    1066   406.4 1086.01   424.2 1091.17   434.9 1096.38
#Mann= 3 ,-1,0
       0      .1       0   121.8    .045       0   143.5      .1       0
Bank Sta=121.8,143.5
XS Rating Curve= 0 ,0
Exp/Cntr(USF)=0,0
Exp/Cntr=0.3,0.1

Type RM Length L Ch R = 1 ,20956   ,497.9,504.5,513.1
XS GIS Cut Line= 4
1670145.05231463426946.4113564821670239.03981199426908.816357541
1670505.09672757426879.8971275861670663.50675734426759.545791769
#Sta/Elev= 30
       0 1073.14     6.9  1069.5    24.8 1058.36    46.4 1042.53    67.9 1025.09
    80.7 1017.28   106.6 1005.95   122.4 1000.19   150.6  994.44   166.7  989.61
   174.7  988.35   190.8   988.5  196.87989.7481   202.9  991.62   210.9   991.8
     223  993.67   271.3  997.41   295.4  998.75   323.6  998.77   335.7 1001.13
     381 1002.58   393.4 1004.53   422.9 1014.58   440.5  1022.6   453.3 1032.34
   461.9 1038.15   487.6 1050.37   506.6 1060.81   533.1 1069.36   567.8  1081.9
#Mann= 3 ,-1,0
       0      .1       0   166.7    .045       0  196.87      .1       0
Bank Sta=166.7,196.87
XS Rating Curve= 0 ,0
Exp/Cntr(USF)=0,0
Exp/Cntr=0.3,0.1

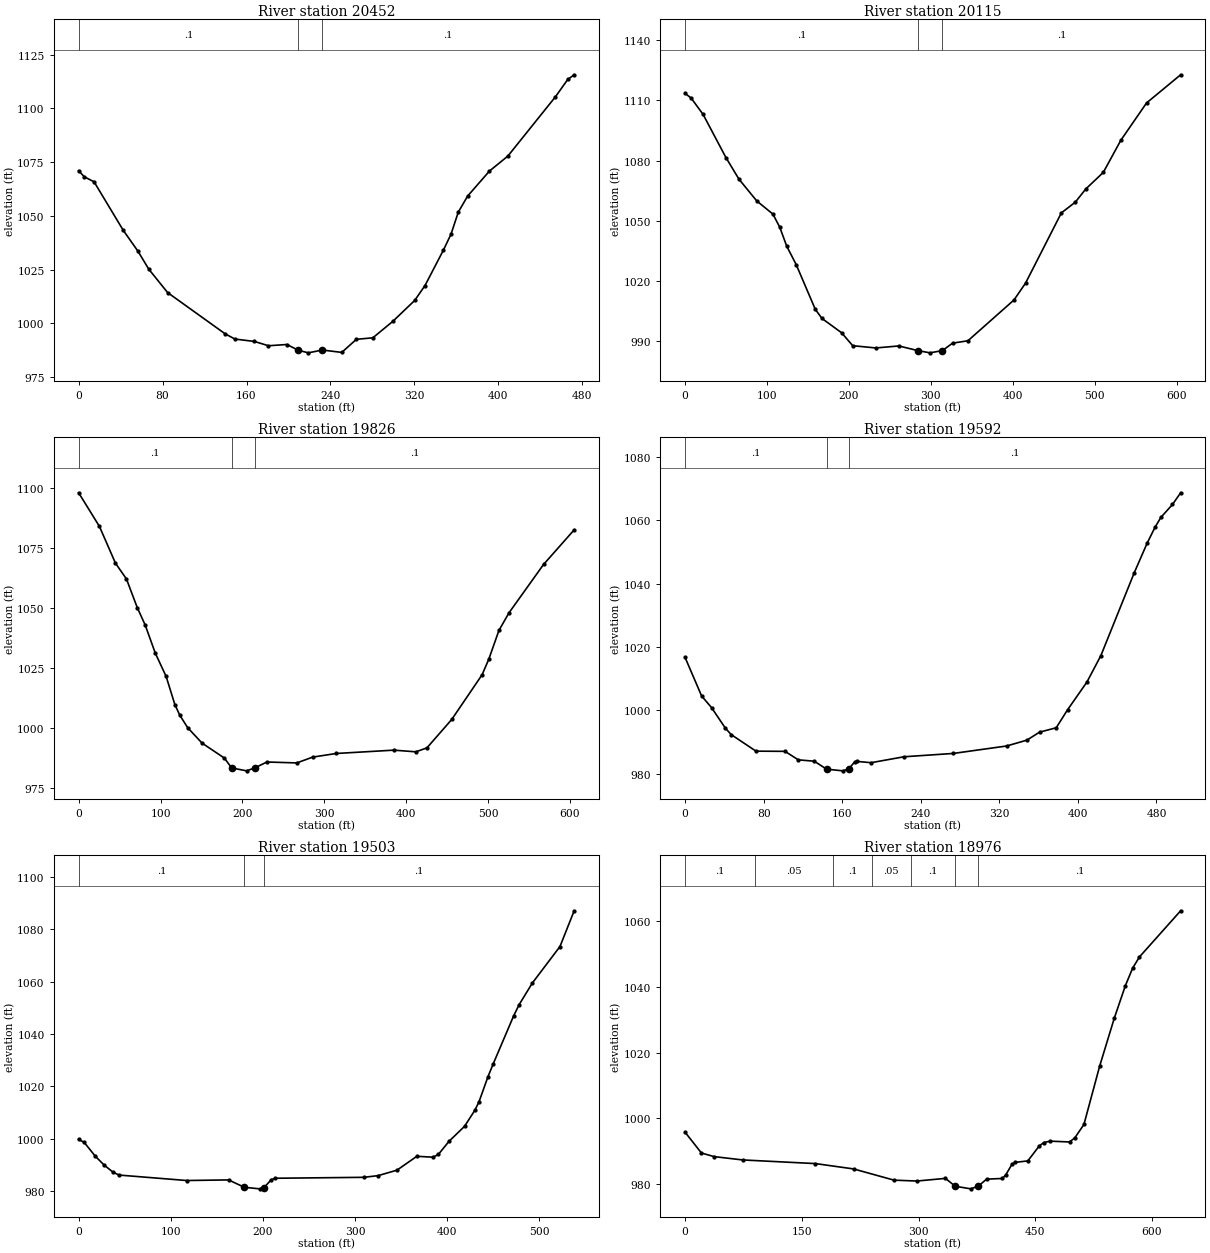
Type RM Length L Ch R = 1 ,20452   ,335.6,336.5,336.5
XS GIS Cut Line= 2
1670071.40316997427233.8434248711670479.48563711427471.623760055
#Sta/Elev= 30
       0 1071.03     5.4 1068.19    14.7 1065.87    42.5  1043.3    56.4 1033.66
    66.8 1025.23    84.8  1014.3   139.7  995.07     149  992.65   167.5  991.55
   180.9  989.54   198.5  990.12   209.2  987.48   218.9  986.24   232.3  987.55
   250.8  986.44   264.7  992.53   280.4  993.24   299.3 1000.83   320.3 1010.63
   330.1 1017.55   347.7  1034.1   354.9 1041.47   361.9  1051.8   370.8 1059.25
   391.5 1070.85   409.1 1077.84   454.5 1105.48   466.2 1113.52   472.3 1115.69
#Mann= 3 ,-1,0
       0      .1       0   209.2    .045       0   232.3      .1       0
Bank Sta=209.2,232.3
XS Rating Curve= 0 ,0
Exp/Cntr(USF)=0,0
Exp/Cntr=0.3,0.1

Type RM Length L Ch R = 1 ,20115   ,282.4,289.4,279.8
XS GIS Cut Line= 3
1669841.46434945427476.6896942061670205.84664688427699.223168708
1670372.42141142 427761.68870541
#Sta/Elev= 30
       0 1113.54     7.4 1111.19    21.9 1103.09      50 1081.38    65.8 1070.68
    87.5 1059.83   107.2 1053.27   115.6 1046.68     124 1037.31   135.7 1027.98
   158.9 1005.75   167.1 1001.16     191  994.04   204.6  987.57   232.8  986.44
   260.9  987.44   284.1  985.11     299     984  314.04 985.122   326.5  988.83
   345.3  990.04   401.5 1010.41   415.6 1018.81   459.3 1053.87   476.3 1059.22
   489.2 1065.85   510.5 1074.09   531.9 1090.13   563.3 1108.77   604.9 1122.83
#Mann= 3 ,-1,0
       0      .1       0   284.1    .045       0  314.04      .1       0
Bank Sta=284.1,314.04
XS Rating Curve= 0 ,0
Exp/Cntr(USF)=0,0
Exp/Cntr=0.3,0.1

Type RM Length L Ch R = 1 ,19826   ,234.9,234.1,231.8
XS GIS Cut Line= 3
1669726.97503478427718.0100231391670056.05418381427868.078690452
1670294.02021341427816.626575945
#Sta/Elev= 30
       0 1098.12    25.4 1084.09      45 1068.74    58.4 1062.17    71.6 1050.22
    81.3 1042.94    93.6 1031.24   106.8 1021.56   117.5 1009.81   123.5 1005.36
   133.1 1000.17   150.7  993.72   177.9  987.49   186.9  983.36   205.1  982.15
   215.4  983.42   229.9  985.84   266.4  985.45   285.7  987.87   314.6  989.39
   384.9  990.78   411.8  990.08   425.3  991.73   455.6 1003.58   492.7 1022.24
   500.9 1028.76   513.2 1040.69   525.4    1048   567.7 1068.22   605.1 1082.66
#Mann= 3 ,-1,0
       0      .1       0   186.9    .045       0   215.4      .1       0
Bank Sta=186.9,215.4
XS Rating Curve= 0 ,0
Exp/Cntr(USF)=0,0
Exp/Cntr=0.3,0.1

Type RM Length L Ch R = 1 ,19592   ,88,88.1,88.9
XS GIS Cut Line= 5
1669655.87514452427915.163397375 1669702.0177449427975.661473424
1669809.68381244 428001.808946971669977.84795603428053.078502943
 1670073.7220257428157.668397129
#Sta/Elev= 30
       0 1016.67    16.8 1004.54    26.9 1000.86    41.1  994.33      47  992.32
    72.2  987.11   101.7  987.05   115.3  984.37   131.5  983.94   144.1  981.43
   160.6   980.9  166.43981.4614   172.9  983.79   174.6  983.89   189.4  983.47
   222.9  985.34   273.1  986.39   327.4  988.74     348  990.58   360.9   993.1
   377.9  994.49   389.4 1000.14   409.2 1008.93   423.4 1017.28   457.3 1043.36
   470.5 1052.75   478.5 1057.75   484.4 1060.84   496.3 1064.95   504.6 1068.64
#Mann= 3 ,-1,0
       0      .1       0   144.1    .045       0  166.43      .1       0
Bank Sta=144.1,166.43
XS Rating Curve= 0 ,0
Exp/Cntr(USF)=0,0
Exp/Cntr=0.3,0.1

Type RM Length L Ch R = 1 ,19503   ,515.5,527.6,538.2
XS GIS Cut Line= 5
1669594.86437291427956.1790421541669688.68766034428058.718154101
1669782.51094778428084.8656276471669906.58327323 428117.67814347
1670025.01594753428243.801251165
#Sta/Elev= 30
       0   999.7     5.9  998.65    18.1  993.31    27.6  989.96    37.4  987.19
    43.9  986.11   117.2  984.03   162.7  984.26   179.9  981.43   196.5  980.85
  201.24981.3604     209  984.33   213.1  984.89   309.4  985.25   324.9  985.89
   345.4  987.98     367  993.28   384.5  992.94   390.3  993.97     402  999.05
   418.8 1004.75   430.1 1010.97   434.5 1014.16   444.2 1023.72   449.9 1028.63
   472.1 1046.98     478 1051.22   492.3 1059.47   522.3 1073.42   537.7 1087.07
#Mann= 3 ,-1,0
       0      .1       0   179.9    .045       0  201.24      .1       0
Bank Sta=179.9,201.24
XS Rating Curve= 0 ,0
Exp/Cntr(USF)=0,0
Exp/Cntr=0.3,0.1

Type RM Length L Ch R = 1 ,18976   ,504,492.8,462.8
XS GIS Cut Line= 3
1669278.51538605427979.9168303381669374.91281924428483.325648069
1669480.23594068428549.375741175
#Sta/Elev= 30
       0  995.83      21  989.51    37.3  988.42    73.9  987.41   167.6   986.3
   216.5  984.68   268.5  981.27   297.9     981   334.6  981.81   347.1  979.42
   367.2  978.63  376.91979.4603   387.5  981.58   407.9  981.78   412.1  982.87
   420.1  986.07   424.2  986.67   440.5  987.12   455.1  991.63   460.8  992.67
     469  993.12   494.1  992.87   500.9  994.12   512.6  998.18   532.9 1015.98
   551.7 1030.53   565.9 1040.37   575.2 1045.67   583.9 1049.06   636.9  1063.1
#Mann= 7 ,-1,0
       0      .1       0      90     .05       0     190      .1       0
     240     .05       0     290      .1       0   347.1    .045       0
  376.91      .1       0
Bank Sta=347.1,376.91
XS Rating Curve= 0 ,0
Exp/Cntr(USF)=0,0
Exp/Cntr=0.3,0.1

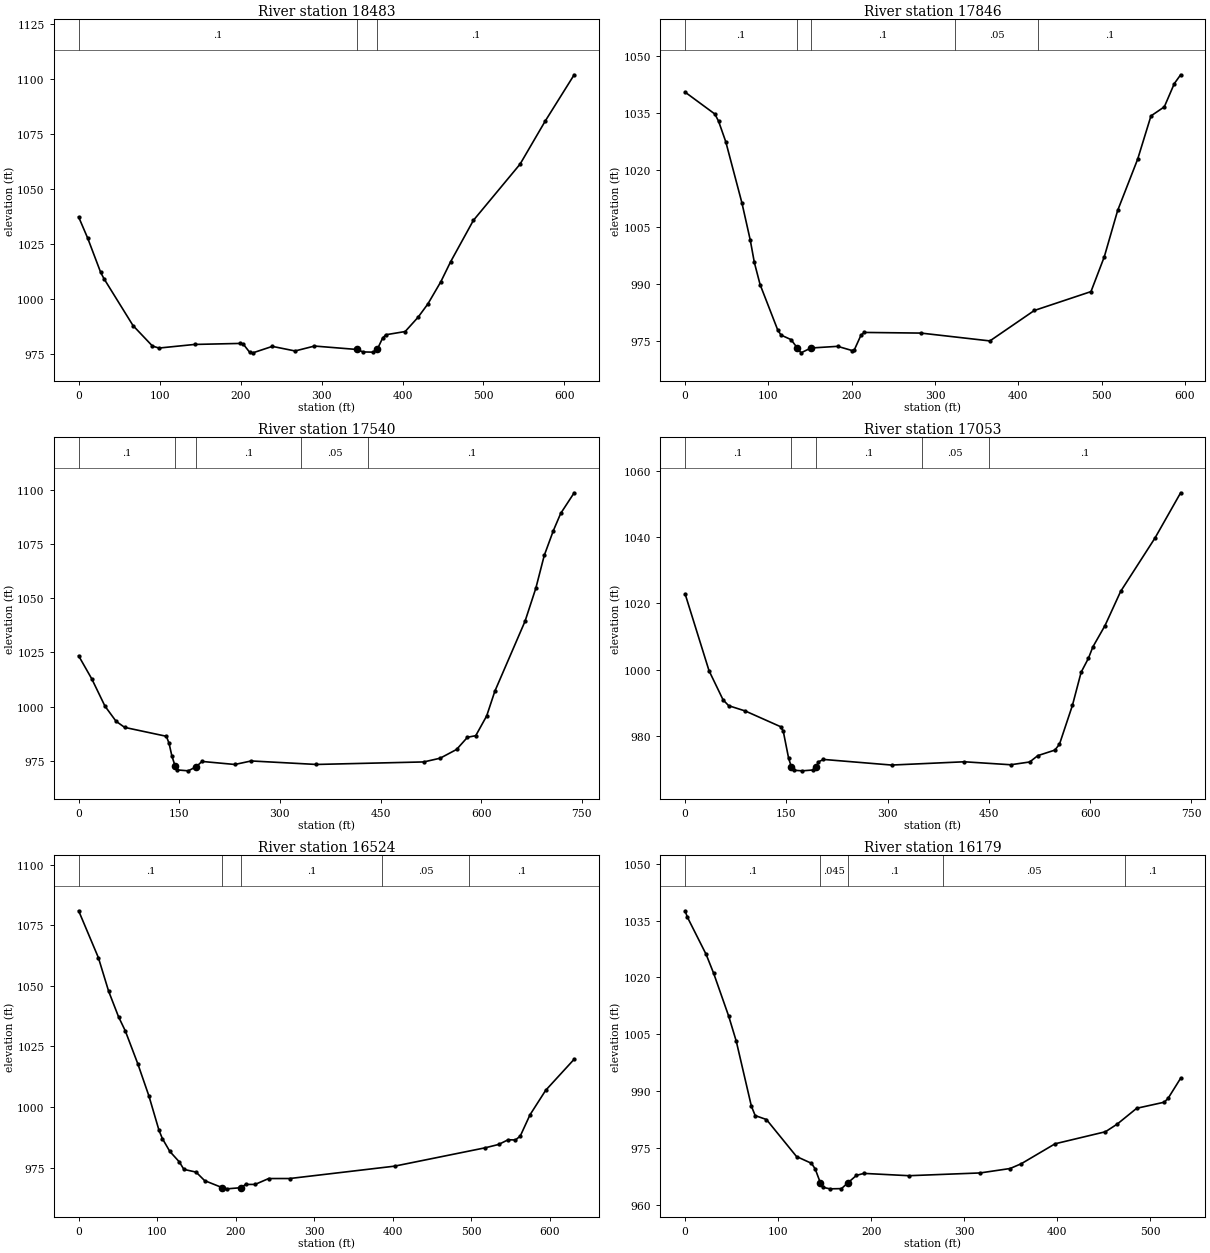
Type RM Length L Ch R = 1 ,18483   ,624.5,637.1,630.6
XS GIS Cut Line= 3
1668940.95295752428672.9444876381669405.08874692428660.448524077
1669551.47003434428640.812009911
#Sta/Elev= 30
       0 1037.27    11.2 1027.66    27.2 1012.14    31.2 1009.33    67.2  987.98
    91.2   978.7    99.2  977.79   143.2  979.43   199.2  979.89   203.2  979.64
   211.2  975.89   215.2  975.62   239.2  978.55   267.3  976.47   291.3   978.7
   343.3  977.16   351.3  976.04   363.3  975.93   368.8  977.19   375.3  982.22
   379.3  983.82   403.3  985.29   419.3  991.81   431.3   997.8   447.3 1007.87
   459.3 1016.88   487.5 1035.72   545.2 1061.26   576.3 1080.83     612  1101.8
#Mann= 3 ,-1,0
       0      .1       0   343.3    .045       0   368.8      .1       0
Bank Sta=343.3,368.8
XS Rating Curve= 0 ,0
Exp/Cntr(USF)=0,0
Exp/Cntr=0.3,0.1

Type RM Length L Ch R = 1 ,17846   ,303.6,305.9,303.9
XS GIS Cut Line= 4
1668911.61744032429026.8459456171668979.09564355429057.371799458
1669398.42447789429063.7982950041669499.64178273 429065.40491889
#Sta/Elev= 30
       0 1040.47    35.7 1034.72    40.1 1032.87    48.8 1027.44    68.2 1011.36
    78.2  1001.6    83.1  995.72      90  989.91   111.1  978.01   115.1  976.64
   127.1  975.45   134.8 973.224   139.1  971.97     151973.2393   183.1  973.68
   200.3  972.58   203.1  972.76   211.1  976.62   215.1  977.33   283.1  977.16
   365.8   975.1   419.1   983.1   487.1  988.06   503.1  997.22   519.1 1009.37
   543.1 1022.84   559.1 1034.22   575.1  1036.6   587.1 1042.71   594.7 1045.03
#Mann= 5 ,-1,0
       0      .1       0   134.8    .045       0     151      .1       0
  324.06     .05       0  424.06      .1       0
Bank Sta=134.8,151
XS Rating Curve= 0 ,0
Exp/Cntr(USF)=0,0
Exp/Cntr=0.3,0.1

Type RM Length L Ch R = 1 ,17540   ,489.6,487,480.3
XS GIS Cut Line= 4
1668824.47453511429264.3588290951668874.45838935429316.127820989
1669408.21454716429423.2360800811669527.81876981429448.228007202
#Sta/Elev= 30
       0 1023.46    19.7 1012.78    39.2 1000.32    55.8  993.32    68.6  990.51
   130.8  986.41   134.8  983.13   138.9  977.44   143.8972.6857   147.1  970.93
   163.4  970.51   175.6  972.49   175.6   972.5   183.8  974.84   232.8  973.44
   257.2  975.06   354.3  973.45   514.3  974.61   538.7  976.32   563.2  980.34
   579.5  985.97   591.8  986.69   608.1  995.79   620.3 1007.18   665.3 1039.39
   681.4 1054.62   693.9 1069.66   707.5  1081.1   718.4    1089   738.5 1098.51
#Mann= 5 ,-1,0
       0      .1       0   143.8    .045       0   175.6      .1       0
  331.96     .05       0  431.96      .1       0
Bank Sta=143.8,175.6
XS Rating Curve= 0 ,0
Exp/Cntr(USF)=0,0
Exp/Cntr=0.3,0.1

Type RM Length L Ch R = 1 ,17053   ,535.1,529.3,518.3
XS GIS Cut Line= 4
1668781.98570881429843.5216330711668859.12128635429821.482896632
1669374.82771901429781.8131710421669458.57491748429673.823362493
#Sta/Elev= 30
       0 1022.91    35.5  999.64    56.3  990.84    64.6  989.08    89.2  987.48
   141.4  982.74   145.4  981.38   153.4  973.16   157.4   970.6   161.5  969.55
   173.5  969.38   189.5  969.64   194.2970.5629   197.6   972.1     205  972.83
   305.9  971.13   413.6  972.12   482.4  971.22   510.5  972.06   522.5  973.98
   547.7  975.65   554.6  977.43   573.8  989.19   586.7  999.21   597.5 1003.43
   604.1 1006.88   622.1 1013.34   645.2 1023.65   696.2 1039.84   734.1 1053.49
#Mann= 5 ,-1,0
       0      .1       0   157.4    .045       0   194.2      .1       0
  350.22     .05       0  450.22      .1       0
Bank Sta=157.4,194.2
XS Rating Curve= 0 ,0
Exp/Cntr(USF)=0,0
Exp/Cntr=0.3,0.1

Type RM Length L Ch R = 1 ,16524   ,334.3,344.9,344
XS GIS Cut Line= 5
1668980.70907101430326.5447709271669148.60077053430261.408693317
1669176.55808826430244.0556805651669283.90962081430235.668842085
1669574.01741978430126.097616249
#Sta/Elev= 30
       0 1081.03    25.1 1061.71    38.2 1047.81    50.8 1037.26    59.4 1031.44
    75.3 1017.87    89.5 1004.54   102.3  990.39   106.6  986.97   116.1  981.66
   128.1  977.37     134  974.25   149.5  973.13   160.4  969.61183.0067966.6868
   188.9  966.22206.9282 966.699   212.5  968.05   224.6  968.04   241.9  970.47
   268.7  970.48   402.1  975.58   517.6  983.17   534.7  984.55   546.7  986.48
   556.1   986.4   562.2  988.03   574.6   996.8   594.5 1006.89   630.8 1019.74
#Mann= 5 ,-1,0
       0      .1       0183.0067    .045       0206.9282      .1       0
  386.68     .05       0  496.68      .1       0
Bank Sta=183.0067,206.9282
XS Rating Curve= 0 ,0
Exp/Cntr(USF)=0,0
Exp/Cntr=0.3,0.1

Type RM Length L Ch R = 1 ,16179   ,513.3,521.9,526.5
XS GIS Cut Line= 4
1669057.85803253430522.5041423671669143.54463981430536.785243579
1669466.65455473430499.2973528971669580.90336443430461.809462215
#Sta/Elev= 30
       0 1037.61     2.3    1036    22.6 1026.09    30.7 1021.08    46.9 1009.73
      55 1003.13    71.2  986.01    75.3  983.51    87.4  982.47   119.7   972.7
   135.8   970.9   139.8   969.4   145.3  965.77   147.8  964.58   155.6  964.16
     168  964.22   174.8965.7203   184.1  967.72   192.1  968.24   240.5  967.63
     317  968.36   349.2  969.53   361.3  970.81   397.5  976.06   451.6  979.24
   464.2  981.25   485.2  985.44   514.7  987.04   518.9  988.06   532.4  993.38
#Mann= 5 ,-1,0
       0      .1       0   145.3    .045       0   174.8      .1       0
  276.87     .05       0  472.15      .1       0
Bank Sta=145.3,174.8
XS Rating Curve= 0 ,0
Exp/Cntr(USF)=0,0
Exp/Cntr=0.3,0.1

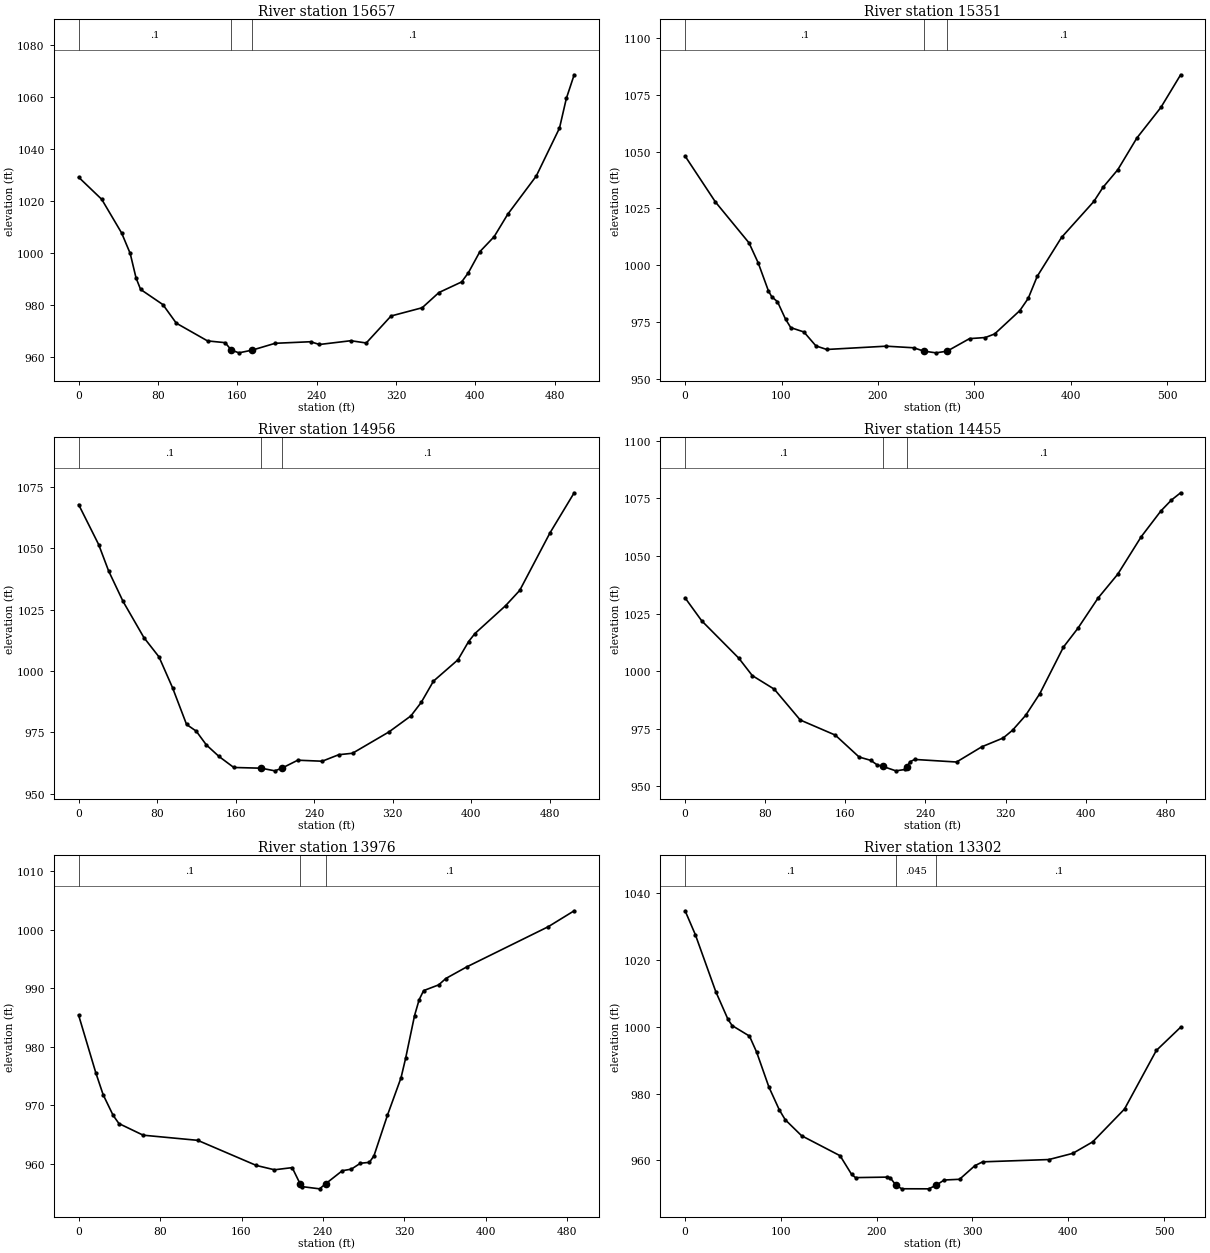
Type RM Length L Ch R = 1 ,15657   ,303.2,305.7,305.6
XS GIS Cut Line= 3
1669000.73362768430788.4896524441669332.76923087430961.648004643
1669434.52207701431034.838648355
#Sta/Elev= 30
       0 1029.27    23.3 1020.76    43.4 1007.79      52  999.96    57.9  990.54
    62.5  986.12      85  980.28    98.5  973.14     130  966.32   147.8  965.64
  154.03962.7852   161.7  961.73   175.2  962.79   198.2   965.4   233.9     966
   242.9  964.94   274.5  966.39   290.1  965.52   315.1   975.9   346.5  979.07
   363.4  984.92   386.3     989   393.1  992.54   404.7 1000.64   419.1 1006.41
   432.8 1015.03   461.6 1029.74     485 1048.16   491.9 1059.56   499.8 1068.66
#Mann= 3 ,-1,0
       0      .1       0  154.03    .045       0   175.2      .1       0
Bank Sta=154.03,175.2
XS Rating Curve= 0 ,0
Exp/Cntr(USF)=0,0
Exp/Cntr=0.3,0.1

Type RM Length L Ch R = 1 ,15351   ,394.8,395,395.5
XS GIS Cut Line= 3
 1668840.2344563430997.0212758431669163.54271985431203.303848908
1669268.66749266431280.659813807
#Sta/Elev= 30
       0 1048.04    31.4  1027.9    66.3 1009.89    75.8 1001.13    86.5  988.71
      90  986.14    95.8  984.06   104.2  976.36   109.6  972.64   123.2  970.74
   135.7  964.61   146.9  963.04   208.6  964.49   237.1  963.78   247.7962.2995
   260.3  961.56   271.8   962.3     295   967.8   311.4  968.29   321.1  969.87
   347.2  980.13   355.9   985.5   365.2  995.15   390.5 1012.31     424  1028.1
   433.4 1034.26   448.8 1042.04   468.6 1055.98   493.5 1069.41     514 1083.77
#Mann= 3 ,-1,0
       0      .1       0   247.7    .045       0   271.8      .1       0
Bank Sta=247.7,271.8
XS Rating Curve= 0 ,0
Exp/Cntr(USF)=0,0
Exp/Cntr=0.3,0.1

Type RM Length L Ch R = 1 ,14956   ,499,501.1,499.7
XS GIS Cut Line= 4
1668628.18062979431260.7696274361668707.52008097431324.241188379
1668907.85219519431443.2503651471669038.76228964431552.342110518
#Sta/Elev= 30
       0 1067.73    20.4 1051.47    30.6 1040.67    45.3 1028.28    66.5 1013.58
    81.9  1005.7    95.7  993.15     110  978.18   119.8  975.49   130.2  969.84
   143.1  965.14   158.1  960.67     186  960.38     200   959.3   207.3  960.42
   223.3  963.63   248.2  963.22   265.1  965.87   279.1  966.46   316.3  975.16
   338.6  981.67   349.1  987.15   361.6  995.83   386.6 1004.54   397.4 1011.95
   403.9 1015.23   435.1 1026.56   449.5 1032.78   480.3 1056.17     505 1072.54
#Mann= 3 ,-1,0
       0      .1       0     186    .045       0   207.3      .1       0
Bank Sta=186,207.3
XS Rating Curve= 0 ,0
Exp/Cntr(USF)=0,0
Exp/Cntr=0.3,0.1

Type RM Length L Ch R = 1 ,14455   ,477.1,478.9,474.8
XS GIS Cut Line= 4
1668375.53202118431653.7114220821668481.34214125 431741.38266443
1668683.89294254431862.3085159451668783.65677004431931.840880566
#Sta/Elev= 30
       0 1031.85    16.6  1021.9    53.6  1005.7    67.1  998.13    89.1  992.22
     115  978.85     150   972.3   173.8  962.78   185.5  961.33   191.9  959.34
   197.2  958.75   210.5  956.79   219.8  957.39   221.7958.5895   224.5  960.67
   229.2  961.74   271.1  960.62   296.3  967.22   317.7  971.05     327  974.41
   340.1  980.86   354.3  990.33   377.9 1010.53   392.3 1018.67   412.4 1031.76
   432.1 1042.14   455.5 1058.38   475.1 1069.54   485.7 1074.32   494.9 1077.47
#Mann= 3 ,-1,0
       0      .1       0   197.2    .045       0   221.7      .1       0
Bank Sta=197.2,221.7
XS Rating Curve= 0 ,0
Exp/Cntr(USF)=0,0
Exp/Cntr=0.3,0.1

Type RM Length L Ch R = 1 ,13976   ,698.6,674.6,637.1
XS GIS Cut Line= 4
1668093.92926992432026.8477873821668171.28523482432094.286320884
1668397.40267068432203.3780662551668514.42836117432139.906505312
#Sta/Elev= 30
       0   985.4    16.9  975.53    24.1  971.79    33.9  968.26    39.6  966.86
    63.4  964.87     117  963.99   174.6  959.69   192.4  958.95   209.8  959.32
   217.5956.5752     219  956.08   236.7  955.69   242.7  956.56     259  958.79
   267.9  959.06   276.8  960.07   285.6  960.22   290.1  961.33   303.4   968.3
   316.7  974.69   321.2  978.01     330  985.34   334.5  988.05   338.9  989.61
   353.7  990.59   360.7  991.68   381.4  993.68   461.4 1000.55   486.8 1003.27
#Mann= 3 ,-1,0
       0      .1       0   217.5    .045       0   242.7      .1       0
Bank Sta=217.5,242.7
XS Rating Curve= 0 ,0
Exp/Cntr(USF)=0,0
Exp/Cntr=0.3,0.1

Type RM Length L Ch R = 1 ,13302   ,439.1,455.7,468
XS GIS Cut Line= 4
1668491.66195342432694.5374580051668533.53555265432582.139902168
1668557.77816274432350.7331695631668601.85563561432192.054267205
#Sta/Elev= 30
       0 1034.71    10.7 1027.56      32 1010.53    44.8 1002.19    49.1 1000.35
    67.2   997.2    74.7  992.39    87.5  981.94    98.3  975.15   104.5  972.17
   121.6  967.38   161.8  961.39   173.8  955.82   177.9  954.84   211.1  954.99
   214.1  954.81     220952.6062   226.1   951.5   254.3  951.48   262.1  952.56
   270.4  954.12   286.5  954.34   302.5  958.41   310.6  959.56   379.8  960.25
   404.7   962.1   425.5  965.54   458.7  975.36   491.9  992.89   517.3  999.86
#Mann= 3 ,-1,0
       0      .1       0     220    .045       0   262.1      .1       0
Bank Sta=220,262.1
XS Rating Curve= 0 ,0
Exp/Cntr(USF)=0,0
Exp/Cntr=0.3,0.1

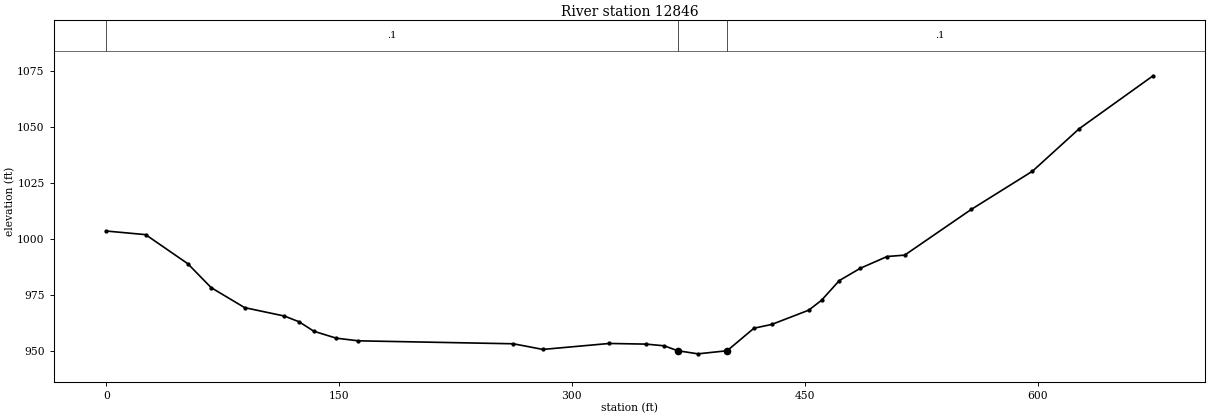
Type RM Length L Ch R = 1 ,12846   ,378.4,385.6,390.6
XS GIS Cut Line= 4
1668623.89437205432776.0807828281668707.64157052432705.556826224
1669091.11558455432458.7229781121669192.49377217432419.053252522
#Sta/Elev= 30
       0 1003.73    25.4 1002.12    52.6  989.12    67.6  978.47    89.2  969.53
   114.8  965.78   124.3   963.2   133.8  958.98   148.2  955.91   162.4  954.72
   262.3   953.4   281.3  950.88   324.1  953.54   347.9  953.25   359.5  952.49
   368.1  950.31   381.2  948.91     400  950.29   417.3  960.35   428.8  962.05
   452.6  968.41   460.8  972.81   472.3  981.63   485.9  987.14   503.1  992.36
   514.4  992.97   557.2 1013.34   596.7 1030.43   626.9 1049.45   674.4 1073.03
#Mann= 3 ,-1,0
       0      .1       0   368.1    .045       0     400      .1       0
Bank Sta=368.1,400
XS Rating Curve= 0 ,0
Exp/Cntr(USF)=0,0
Exp/Cntr=0.3,0.1