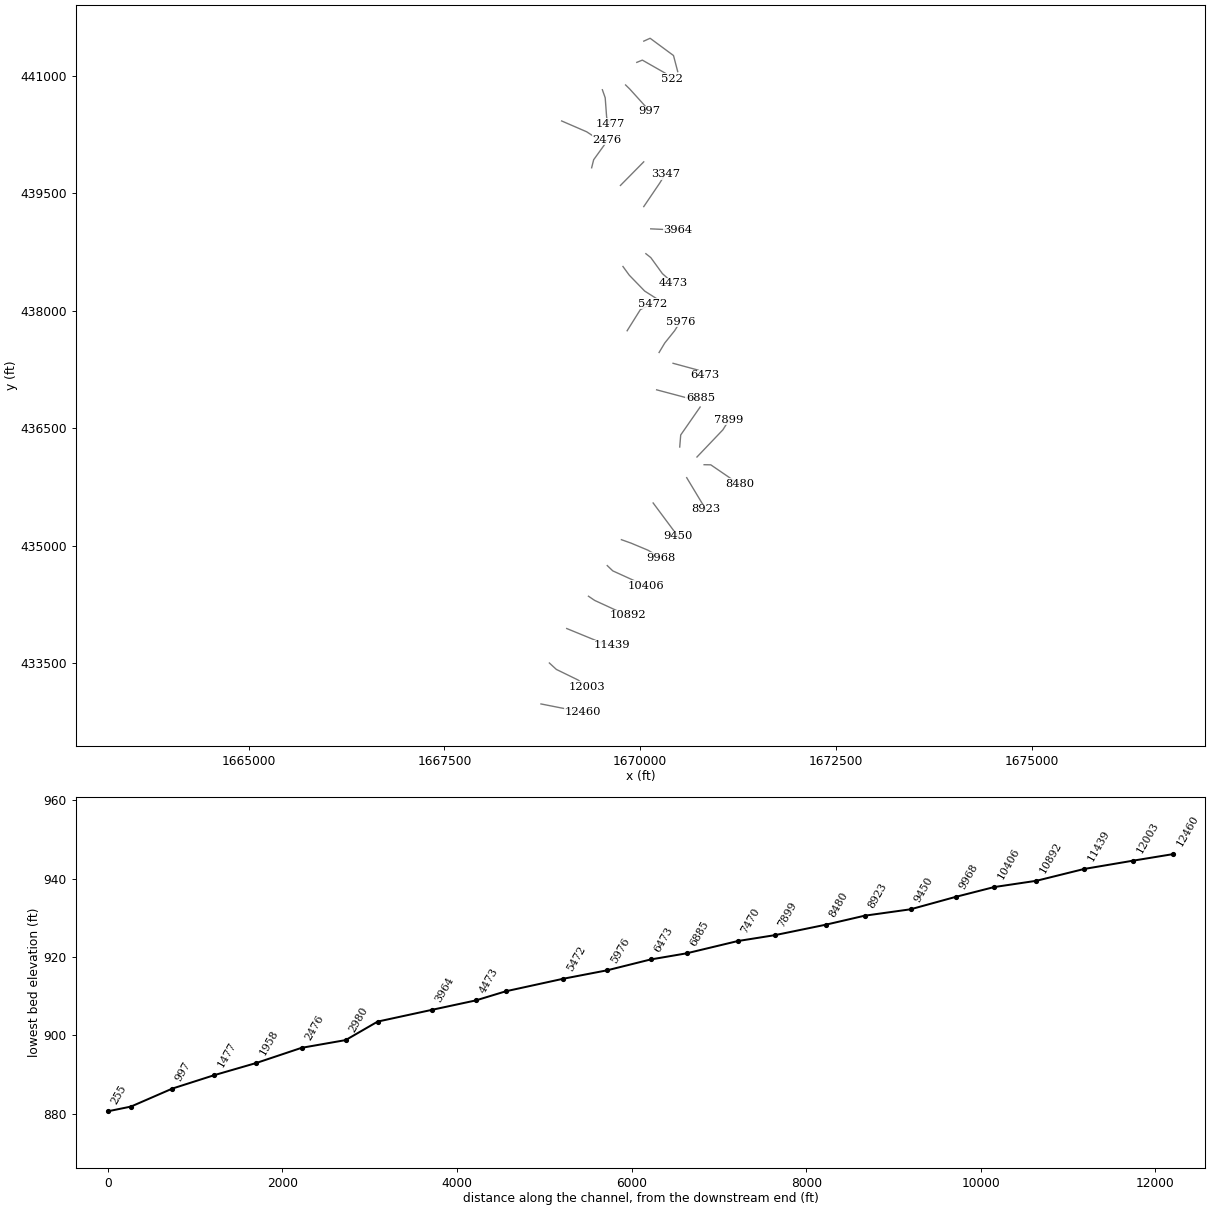
HEC-RAS study KNOBBFK.prj: KNOBBFK

--- KNOBBFK.g01 (geometry) --- (continued)

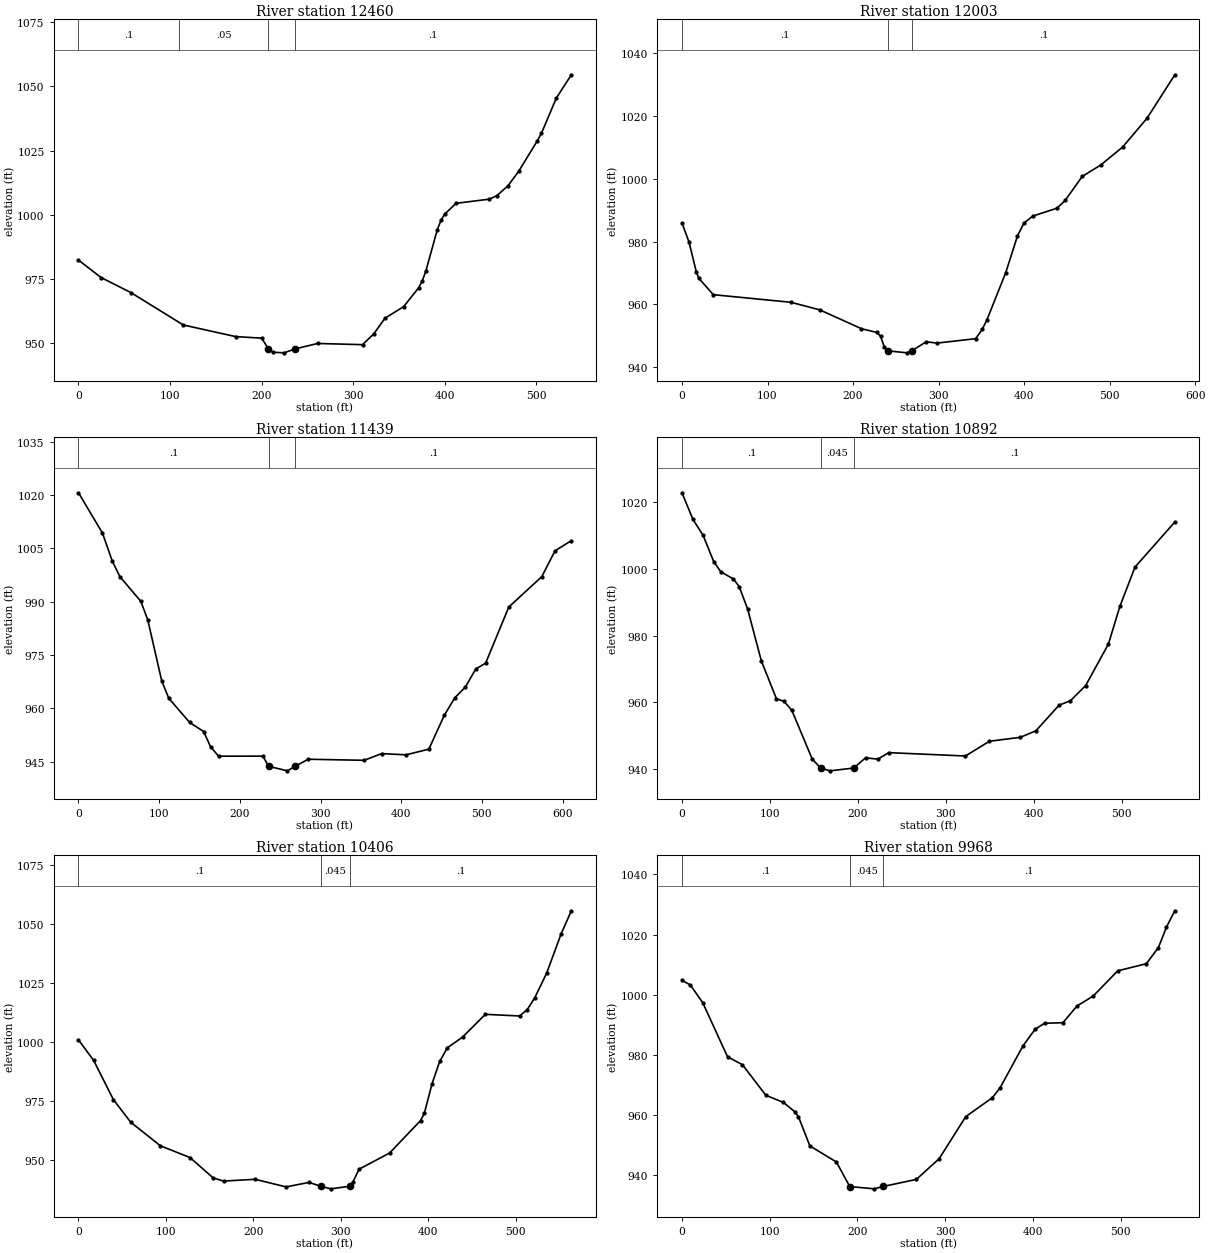
Type RM Length L Ch R = 1 ,12460   ,459.8,457.7,452.1
XS GIS Cut Line= 3
1668731.85175568432980.4396271381669138.86314023 432900.10843282
1669260.25250053432878.686781002
#Sta/Elev= 30
       0  982.34    24.7  975.54    57.3  969.68   114.4  957.09   171.5  952.57
     200  951.95   207.2947.8976   212.3  946.48   224.5  946.24   236.7   947.8
   261.2  949.89   310.1  949.42   322.4  953.62   334.6  959.72     355  964.21
   371.3  971.53   375.4  974.27   379.4  978.26   391.7  994.12   395.8  997.82
   399.8 1000.22   412.2 1004.45   448.6 1006.07   456.8 1007.45   468.9 1011.24
   481.1 1017.18   500.8 1028.69   505.5 1031.75   521.7  1045.4   538.1 1054.49
#Mann= 4 ,-1,0
       0      .1       0     110     .05       0   207.2    .045       0
   236.7      .1       0
Bank Sta=207.2,236.7
XS Rating Curve= 0 ,0
Exp/Cntr(USF)=0,0
Exp/Cntr=0.3,0.1

Type RM Length L Ch R = 1 ,12003   ,561,563.8,563.3
XS GIS Cut Line= 4
1668839.17861848433503.3105234951668928.43550105433421.194191525
1669203.34669939 433287.308867661669322.95092204433198.051985084
#Sta/Elev= 30
       0  985.97     8.3   979.8    16.8  970.33    19.6  968.35    36.6  963.11
   127.5  960.68     161  958.28   209.9  952.26   227.7  951.08   232.2  949.86
   236.6  946.38  240.35945.2221   263.3  944.57     269  945.24   285.5   948.1
   298.1  947.68   343.4  949.08   351.2   952.1   356.7  955.16   378.6  970.15
   392.3  981.83   399.8   985.9   410.1  988.16   438.4  990.67     448  993.14
     468  1000.8   489.6 1004.43   515.3 1010.18   543.9  1019.4   576.3 1033.21
#Mann= 3 ,-1,0
       0      .1       0  240.35    .045       0     269      .1       0
Bank Sta=240.35,269
XS Rating Curve= 0 ,0
Exp/Cntr(USF)=0,0
Exp/Cntr=0.3,0.1

Type RM Length L Ch R = 1 ,11439   ,536.6,547.1,538.5
XS GIS Cut Line= 3
1669060.63146054433943.6344104611669514.84981854433757.186700191
1669631.87550903433731.401378557
#Sta/Elev= 30
       0  1020.6    29.7 1009.28    41.8 1001.43    51.3  997.02    77.3  990.08
    85.9  984.83   103.2  967.67   111.9  962.84   137.8  956.03   155.1  953.49
   163.7  949.19   173.6  946.56   228.6  946.57   235.5 943.717   258.9  942.44
   268.7  943.75   284.8   945.7     354   945.4   375.6  947.28   405.9  946.94
   434.2  948.53   453.4  958.08   466.4  962.99   479.4  965.96   492.3  971.05
   504.6  972.72   533.3  988.49   574.2  997.03   590.6 1004.29   610.8 1007.15
#Mann= 3 ,-1,0
       0      .1       0   235.5    .045       0   268.7      .1       0
Bank Sta=235.5,268.7
XS Rating Curve= 0 ,0
Exp/Cntr(USF)=0,0
Exp/Cntr=0.3,0.1

Type RM Length L Ch R = 1 ,10892   ,484,485.8,483.4
XS GIS Cut Line= 4
1669338.26908672434355.9535396651669417.60853789434302.399410119
1669715.13147982434165.538856835 1669842.0746017434113.968213569
#Sta/Elev= 30
       0  1022.8    12.4 1014.84      24 1010.04      36 1002.19    44.1   999.1
    58.5  996.95      65  994.67    74.6  987.95    90.2  972.38   107.3  961.08
   116.1  960.23   124.9  957.54     148  942.97   157.6  940.27   168.4  939.42
   195.5  940.28   208.6  943.33   222.7  942.92     235  944.88   322.2  943.87
   349.4  948.29   384.7  949.48   402.3  951.43   428.6   959.1   441.5  960.44
   458.8  964.98   484.7  977.44   497.7   988.7   514.9 1000.51   560.2 1014.04
#Mann= 3 ,-1,0
       0      .1       0   157.6    .045       0   195.5      .1       0
Bank Sta=157.6,195.5
XS Rating Curve= 0 ,0
Exp/Cntr(USF)=0,0
Exp/Cntr=0.3,0.1

Type RM Length L Ch R = 1 ,10406   ,434.8,437.5,436.1
XS GIS Cut Line= 4
1669578.25819304434747.0916104531669648.94964404434679.613407225
1669934.92869581434549.4768724291670074.70497393434490.031788633
#Sta/Elev= 30
       0 1000.93    17.3  992.25    39.9  975.64    59.7  966.07    93.7  956.04
   127.6  951.07   153.9  942.48   165.9   941.1   202.1  941.85   237.4  938.63
   263.8  940.54     277   938.9   288.6  937.81   310.2 938.902   313.9  940.63
   320.9  946.12     356  953.02   391.3  966.75   395.6  969.78   404.4   982.3
   413.2   991.8   421.9  997.56   439.3 1002.09   465.4 1011.76   504.5 1011.07
   513.2  1013.7   521.9 1018.74   535.5 1029.18   552.3 1046.02   563.8 1055.65
#Mann= 3 ,-1,0
       0      .1       0     277    .045       0   310.2      .1       0
Bank Sta=277,310.2
XS Rating Curve= 0 ,0
Exp/Cntr(USF)=0,0
Exp/Cntr=0.3,0.1

Type RM Length L Ch R = 1 ,9968    ,527.9,518.6,508.8
XS GIS Cut Line= 4
1669759.21822771435077.8274904921669882.63515176435033.750017614
1670098.61476886434943.3911982161670268.31303944434844.216884243
#Sta/Elev= 30
       0 1004.74     9.4 1003.23    23.6  997.34    51.9  979.29    68.9  976.64
    95.6  966.46   115.6   964.1   128.4  961.02   132.7  959.38   145.7  949.62
     176  944.26   191.2  936.07   219.4  935.32  229.66936.1346   267.1  938.46
   293.1  945.35   323.4  959.36   353.8  965.68   362.5  968.93   388.8  983.01
   402.5  988.46   413.2  990.45   434.2  990.63   450.2  996.21   468.8  999.54
   496.6 1007.91   529.2 1010.27     543 1015.66   552.2 1022.49   561.7  1027.9
#Mann= 3 ,-1,0
       0      .1       0   191.2    .045       0  229.66      .1       0
Bank Sta=191.2,229.66
XS Rating Curve= 0 ,0
Exp/Cntr(USF)=0,0
Exp/Cntr=0.3,0.1

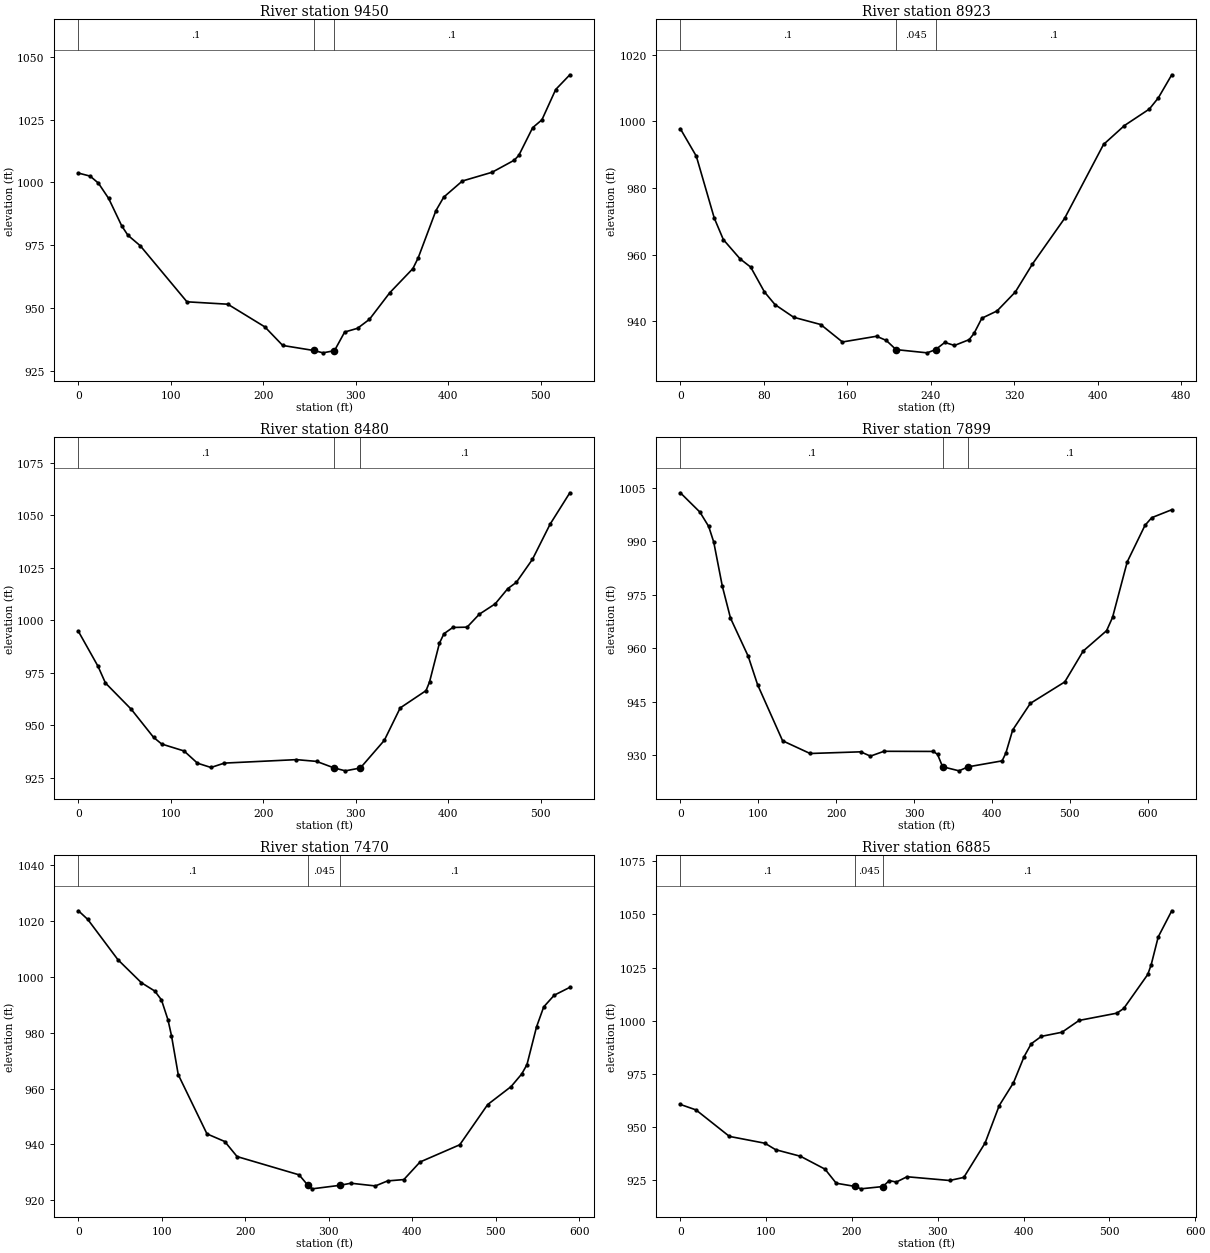
Type RM Length L Ch R = 1 ,9450    ,528.7,527,523.5
XS GIS Cut Line= 2
1670164.15410961435546.7472372041670481.51191433435120.297687117
#Sta/Elev= 30
       0 1003.74    12.7 1002.53    21.6  999.74    32.7  993.64    46.8  982.75
    53.5  978.99    66.9  974.79   117.4  952.47   161.6  951.51   201.7  942.47
     221  935.08   254.5  933.08   264.6  932.14     277  933.01     288  940.42
   301.9  941.91   314.8  945.48   336.8  956.08   361.8  965.69   367.5  969.93
   386.7  988.76   395.2  994.17   415.3 1000.58   447.5 1004.07   471.4 1008.86
   476.4  1010.8   491.4 1021.83   501.4 1024.96   516.3 1037.03   531.6  1042.9
#Mann= 3 ,-1,0
       0      .1       0   254.5    .045       0     277      .1       0
Bank Sta=254.5,277
XS Rating Curve= 0 ,0
Exp/Cntr(USF)=0,0
Exp/Cntr=0.3,0.1

Type RM Length L Ch R = 1 ,8923    ,437.5,443,449.8
XS GIS Cut Line= 2
 1670592.6578876435869.6179910271670835.43660821435466.176881783
#Sta/Elev= 30
       0  997.77    15.3  989.53    32.5  970.95    41.2  964.49    57.3  958.69
    67.4  956.24    80.6  948.77    90.7  944.98   108.6  941.18   134.5     939
   155.3  933.76     188  935.48   197.3  934.23   206.7  931.47   236.5   930.5
   244.5931.4562   253.4  933.62   262.7  932.72   276.7  934.45   281.4  936.32
   288.9  940.89   303.5  943.08     321  948.77   337.4  957.16   368.2  970.86
   405.5  993.05   425.6  998.74   449.4 1003.68     458 1007.03   470.9 1013.97
#Mann= 3 ,-1,0
       0      .1       0   206.7    .045       0   244.5      .1       0
Bank Sta=206.7,244.5
XS Rating Curve= 0 ,0
Exp/Cntr(USF)=0,0
Exp/Cntr=0.3,0.1

Type RM Length L Ch R = 1 ,8480    ,561.9,581.1,603.2
XS GIS Cut Line= 4
1670814.96144666436035.1234899471670900.27317502436033.677528449
1671164.88412911435852.9323412321671274.77720294435792.201958327
#Sta/Elev= 30
       0  994.67    21.2  978.02    29.2  970.09    57.2  957.52    81.2   944.2
      90  940.99   114.2  937.68   128.7  931.86   143.3  929.81   157.8   931.9
   235.7  933.55   257.5  932.71   276.4929.5943   288.6  928.21   304.8  929.56
   330.7  942.73   347.9   958.2   375.8  966.43   379.6  970.55   390.3  989.05
   395.2  993.56   404.8  996.55   420.2  996.69   433.4 1002.85   450.6  1007.8
   464.3  1015.1   473.4 1018.02   490.9 1029.04     510  1045.8   531.3 1060.74
#Mann= 3 ,-1,0
       0      .1       0   276.4    .045       0   304.8      .1       0
Bank Sta=276.4,304.8
XS Rating Curve= 0 ,0
Exp/Cntr(USF)=0,0
Exp/Cntr=0.3,0.1

Type RM Length L Ch R = 1 ,7899    ,423.6,428.2,426.5
XS GIS Cut Line= 3
1670723.65981012 436133.510139481671054.62433071436480.540898937
1671134.95552503436609.070809847
#Sta/Elev= 30
       0 1003.64    25.1  998.22    36.4  994.18    42.9  989.78    53.9   977.4
    64.4  968.44    87.1  957.75    99.2  949.74   131.3  933.99   166.6  930.42
   231.6  930.89   244.1  929.68   261.5  931.04     325     931   330.3  930.16
   336.8   926.7   357.9  925.55   369.3926.6641   413.2  928.35     418  930.51
   426.8  937.02   449.5   944.5   493.7  950.52   517.3  959.18   547.4  964.91
     555  968.62   573.9  984.24   596.7  994.49   605.4  996.65   631.1  998.88
#Mann= 3 ,-1,0
       0      .1       0   336.8    .045       0   369.3      .1       0
Bank Sta=336.8,369.3
XS Rating Curve= 0 ,0
Exp/Cntr(USF)=0,0
Exp/Cntr=0.3,0.1

Type RM Length L Ch R = 1 ,7470    ,599.1,585.6,558.5
XS GIS Cut Line= 3
1670503.67844823436261.3627265571670516.17441179436414.884564588
1670764.30854535436771.912094893
#Sta/Elev= 30
       0 1023.72    11.2 1020.62    47.3 1006.19    75.4  997.94    91.5  994.94
    99.5  991.76   107.3  984.62   111.5  978.95   119.6  964.97     154  943.74
   175.3     941   190.1   935.6   264.4  929.05   274.5  925.46   280.1  924.03
   313.2  925.29   326.5  926.04   355.8  925.07   370.4  926.87   389.9  927.35
   409.3  933.65   456.9  939.83   490.4  954.26   518.4  960.69   531.1  965.19
   537.4  968.54   548.9   982.1   557.5  989.26   570.1  993.45   588.8  996.27
#Mann= 3 ,-1,0
       0      .1       0   274.5    .045       0   313.2      .1       0
Bank Sta=274.5,313.2
XS Rating Curve= 0 ,0
Exp/Cntr(USF)=0,0
Exp/Cntr=0.3,0.1

Type RM Length L Ch R = 1 ,6885    ,409.6,412.3,410.1
XS GIS Cut Line= 3
1670208.79625482436991.422021301 1670597.5595656436888.280734768
1670768.13938563436888.280734768
#Sta/Elev= 30
       0  960.62    18.2  958.05    57.2  945.57    98.6  942.36     111  939.33
     140  936.23   168.6  930.17   181.7  923.54   204.1  922.01   210.4   920.9
   236.1921.9797   243.5  924.78   251.7  924.09   264.2  926.59   313.8  924.83
   330.4  926.28   355.2  942.47   371.7   960.1   388.3  970.83   400.7  983.13
     409  989.17   420.8  992.65   444.8  994.59   464.8 1000.15   508.8 1003.57
   516.8 1005.77   544.8 1021.77   548.8 1026.34     557 1039.44   572.8 1051.75
#Mann= 3 ,-1,0
       0      .1       0   204.1    .045       0   236.1      .1       0
Bank Sta=204.1,236.1
XS Rating Curve= 0 ,0
Exp/Cntr(USF)=0,0
Exp/Cntr=0.3,0.1

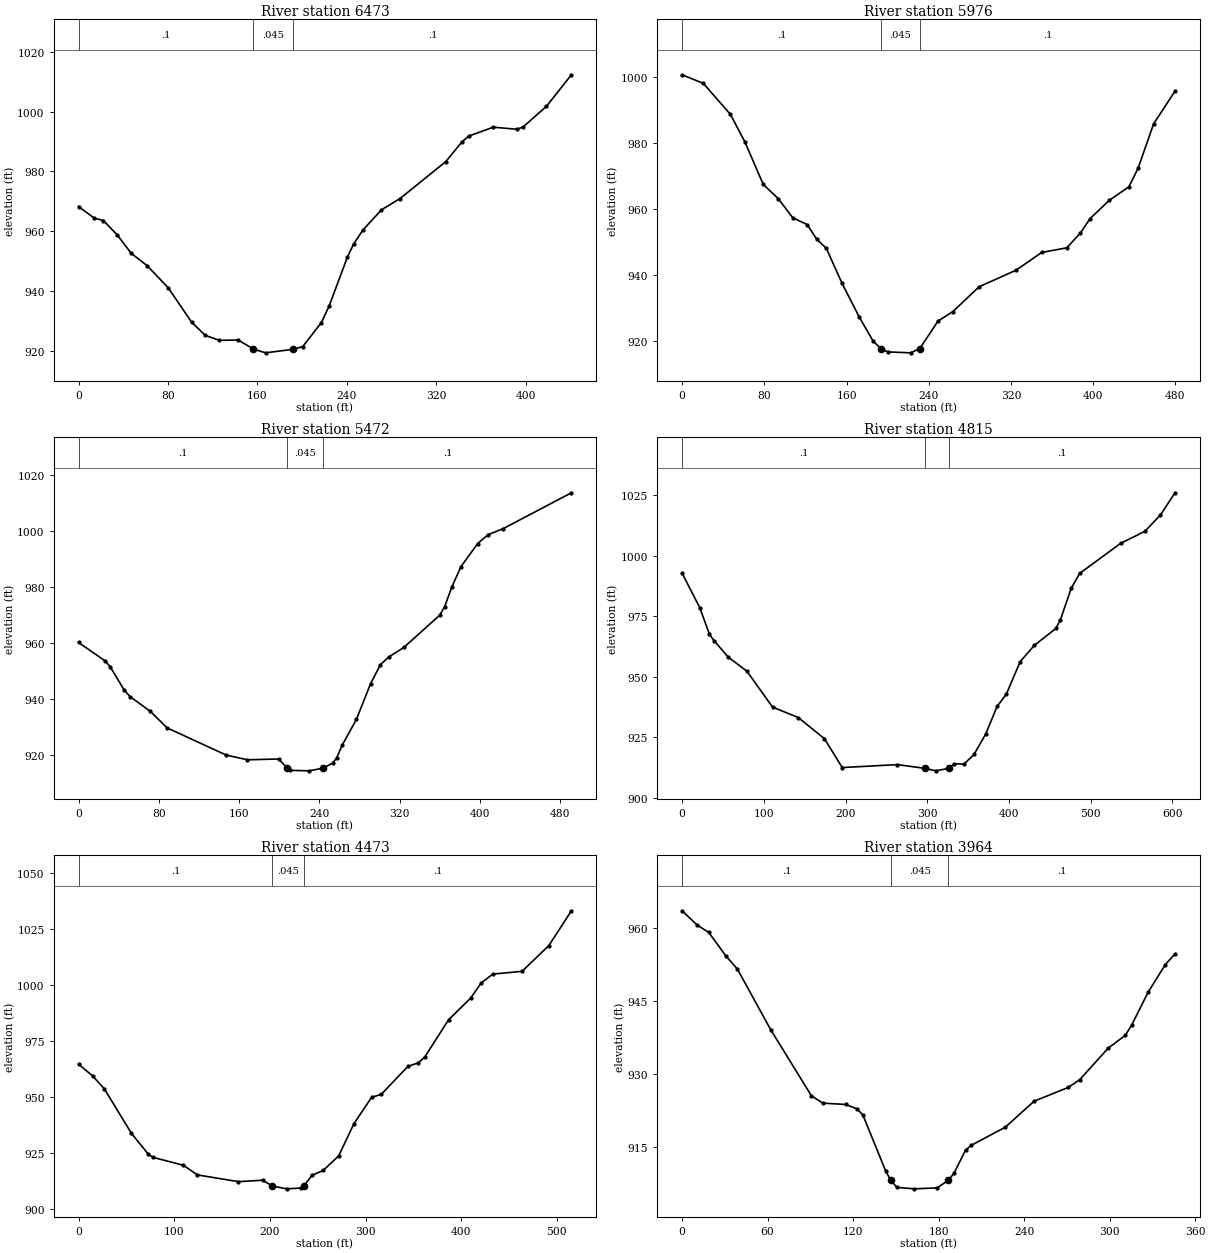
Type RM Length L Ch R = 1 ,6473    ,477,496.6,518.4
XS GIS Cut Line= 3
1670418.55360237437330.1647529521670739.87837965437242.891356655
1670827.15177594437179.419795712
#Sta/Elev= 30
       0  968.21    14.1  964.38    22.3  963.54    34.8  958.68    47.2  952.57
    61.3   948.5    80.4  941.01   101.1  929.61   113.5  925.15     126   923.5
   142.8  923.62  156.48920.5857   167.4  919.33   192.3  920.53   200.6  921.44
   217.2  929.42   224.3  935.09   240.5  951.33   246.2  955.76   254.5  960.43
     271  967.14   287.6  970.91   328.6  983.28   343.1  989.91   349.1  991.79
     371  994.76   392.1  994.07   397.6  994.81   418.6 1001.75   440.9 1012.28
#Mann= 3 ,-1,0
       0      .1       0  156.48    .045       0   192.3      .1       0
Bank Sta=156.48,192.3
XS Rating Curve= 0 ,0
Exp/Cntr(USF)=0,0
Exp/Cntr=0.3,0.1

Type RM Length L Ch R = 1 ,5976    ,502.5,504,506.4
XS GIS Cut Line= 4
1670240.01534974437468.1871013541670312.74317998437589.400151766
1670438.36397768 437745.875180481670511.09180793437862.680483604
#Sta/Elev= 30
       0 1000.62    20.7  998.01      47  988.66    61.1  980.34      79  967.46
    93.5  963.21   107.7  957.39   121.7  955.35     131  950.92   140.4  948.14
   155.6  937.59   172.3  927.45   185.8  920.13   193.6917.8317     200  916.86
   222.3  916.57   231.3  917.86     249  926.18   263.4  929.02     289  936.54
   324.9  941.54   349.9  946.91   374.3  948.32   387.6  952.81     397  957.16
   415.8  962.71   434.7  966.74   443.7  972.37   458.8   985.8   479.6  995.67
#Mann= 3 ,-1,0
       0      .1       0   193.6    .045       0   231.3      .1       0
Bank Sta=193.6,231.3
XS Rating Curve= 0 ,0
Exp/Cntr(USF)=0,0
Exp/Cntr=0.3,0.1

Type RM Length L Ch R = 1 ,5472    ,679.3,657.4,619.1
XS GIS Cut Line= 3
1669832.13849887437745.7572777751670001.83676945438016.833735969
1670156.10792452438091.765439861
#Sta/Elev= 30
       0  960.18    26.9  953.49    31.6   951.5    45.2  943.39    51.3   940.9
    71.7  935.58    88.2  929.74   147.1  920.05   168.4  918.34   199.4  918.64
   208.1  915.44     211  914.59   229.8  914.41     244  915.38   253.4  917.21
   257.4  919.05   262.8  923.53     277  932.75   291.1  945.44   300.9  952.26
   309.6  955.07   324.3  958.39     360  969.88   364.9  972.86   372.2  980.01
   381.2  987.19   397.9  995.43   408.1  998.56   423.1 1000.69   491.3 1013.51
#Mann= 3 ,-1,0
       0      .1       0   208.1    .045       0     244      .1       0
Bank Sta=208.1,244
XS Rating Curve= 0 ,0
Exp/Cntr(USF)=0,0
Exp/Cntr=0.3,0.1

Type RM Length L Ch R = 1 ,4815    ,342.5,341.6,337.7
XS GIS Cut Line= 4
1669778.84730324 438566.053854181669859.82114711438454.714818854
 1670056.4719108438252.2802091711670211.18979106438153.954827325
#Sta/Elev= 30
       0  992.82    21.7  978.56    33.5  967.56    39.2  964.95    56.3  958.23
    79.3  952.36   110.7  937.53   142.2  933.22   174.2  924.49     196  912.56
   263.4  913.78   297.8  912.21   310.3  911.21   326.1  912.21   333.3  914.16
   344.8  913.94   357.2  917.96   371.4   926.3   385.5  937.81   396.8  942.89
   413.8  956.34     431     963   457.4  969.99   462.9  973.53   476.3  986.66
   486.5  992.72   536.6 1005.14   566.4 1010.12   585.4 1016.88   603.2 1026.03
#Mann= 3 ,-1,0
       0      .1       0   297.8    .045       0   326.1      .1       0
Bank Sta=297.8,326.1
XS Rating Curve= 0 ,0
Exp/Cntr(USF)=0,0
Exp/Cntr=0.3,0.1

Type RM Length L Ch R = 1 ,4473    ,494.9,509.3,524.2
XS GIS Cut Line= 4
1670071.52710767438729.6927292611670134.18543924438679.887388783
1670281.99483678438475.8461552141670418.55786713438353.742739849
#Sta/Elev= 30
       0  964.67    14.7  959.42    26.9  953.68    55.3  933.74    72.4  924.69
    77.4  923.03   109.6  919.44   124.2  915.14   166.9  912.11   192.4  912.73
   202.7  910.15   217.5  908.89   232.4  909.25   235.6  910.25   244.2  914.98
   255.7  917.12   271.9   923.6   287.9  938.05   306.4  949.88   316.3   951.1
   344.3  963.67     355  965.25   361.7  967.71   386.8  984.52     410  994.28
   420.8 1000.96     433 1004.96   463.6  1006.2   491.6 1017.71   515.2 1033.29
#Mann= 3 ,-1,0
       0      .1       0   202.7    .045       0   235.6      .1       0
Bank Sta=202.7,235.6
XS Rating Curve= 0 ,0
Exp/Cntr(USF)=0,0
Exp/Cntr=0.3,0.1

Type RM Length L Ch R = 1 ,3964    ,589.1,617.1,633.3
XS GIS Cut Line= 2
1670133.43797389439047.050526512 1670478.9835946439030.725536557
#Sta/Elev= 30
       0  963.54    10.7  960.58    18.7  959.11    30.7  954.27    38.7  951.62
    62.3  939.07    90.8  925.54    98.8  924.05   114.8  923.77   122.8  922.86
   126.8  921.65   142.8  910.17   146.4  908.18   150.8  906.75   162.9  906.45
   178.9  906.64   186.9  908.22   190.9   909.7   198.9  914.39   202.9  915.38
   226.9  919.12     247  924.44     271  927.27     279  928.85     299  935.33
     311  937.96   315.4  940.02     327  946.81   339.1  952.49   345.9  954.69
#Mann= 3 ,-1,0
       0      .1       0   146.4    .045       0   186.9      .1       0
Bank Sta=146.4,186.9
XS Rating Curve= 0 ,0
Exp/Cntr(USF)=0,0
Exp/Cntr=0.3,0.1

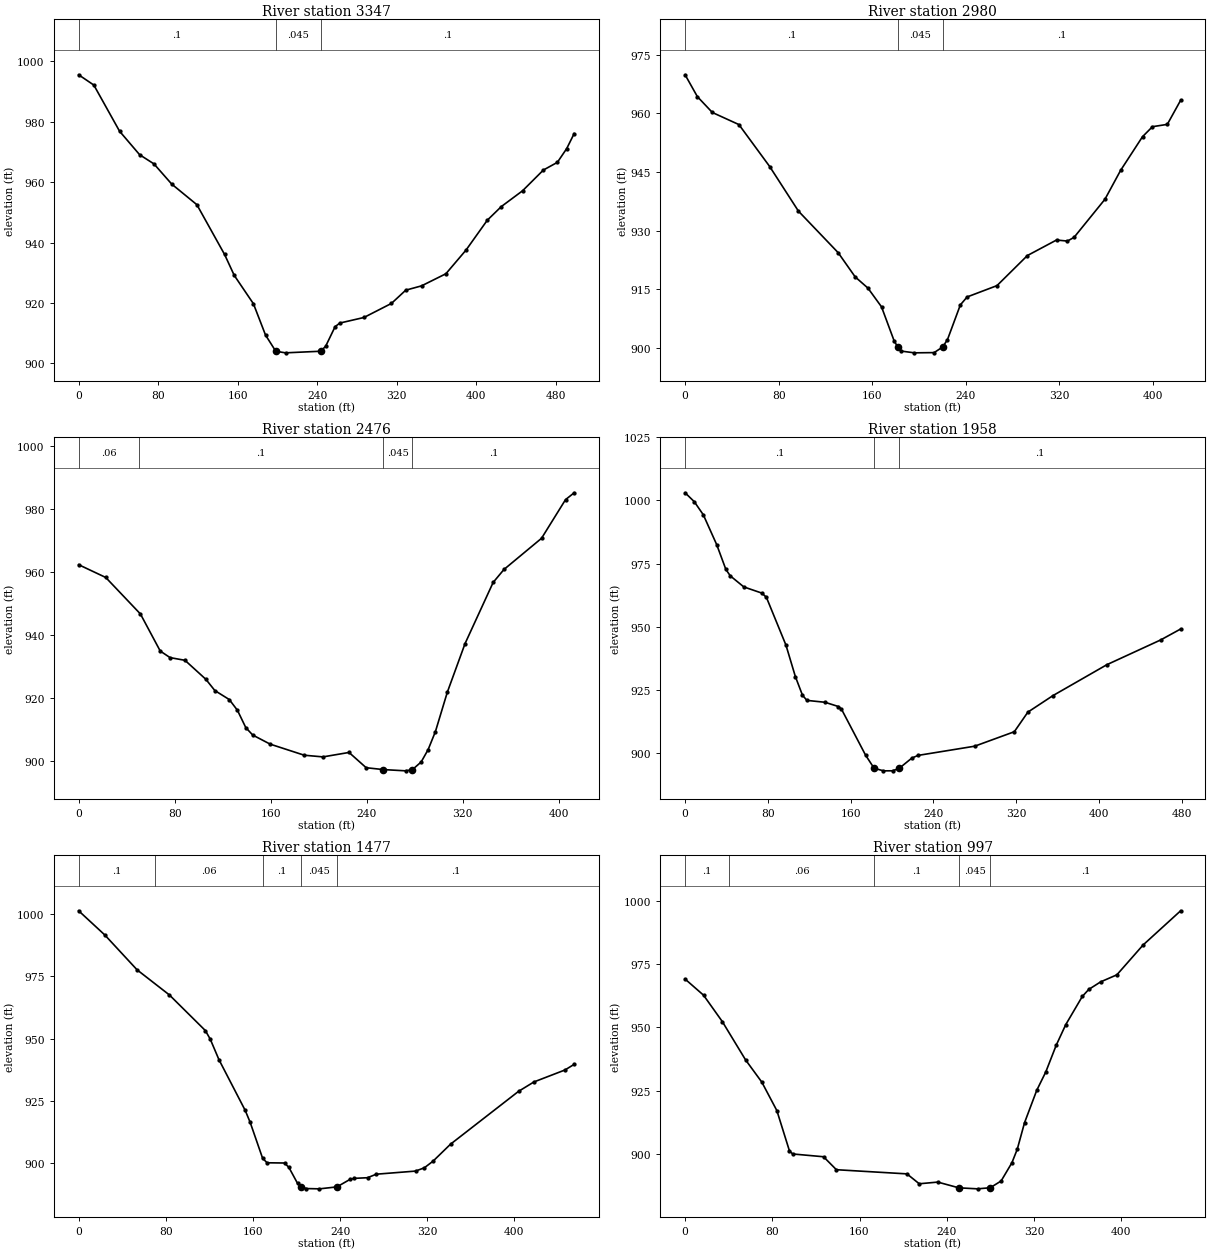
Type RM Length L Ch R = 1 ,3347    ,369.8,366.3,362.5
XS GIS Cut Line= 3
1670044.41372242439330.984002628 1670247.9194147439630.887128084
1670319.32492076439746.921075433
#Sta/Elev= 30
       0  995.59    15.3  992.18    41.2  976.89    61.4   969.1    75.8  966.07
    93.7  959.37     119  952.55   146.9  936.05   156.6  929.13   175.9  919.74
   188.1  909.35  198.41903.9904   208.2  903.47   243.6     904   248.6  905.65
   258.1  912.14   262.9  913.34   287.1  915.18   314.8  919.84   329.2  924.23
   345.1  925.66   369.6  929.67   389.9  937.53   411.3  947.42   425.4  951.93
   446.8  957.17   467.7  964.03   481.8  966.58   491.2  971.15   498.7  976.12
#Mann= 3 ,-1,0
       0      .1       0  198.41    .045       0   243.6      .1       0
Bank Sta=198.41,243.6
XS Rating Curve= 0 ,0
Exp/Cntr(USF)=0,0
Exp/Cntr=0.3,0.1

Type RM Length L Ch R = 1 ,2980    ,501,504.2,506.6
XS GIS Cut Line= 2
1669746.59336673 439601.053074581670044.11630865 439902.54298906
#Sta/Elev= 30
       0  969.83    10.5  964.24    23.3  960.19      46   957.1    72.3  946.38
    96.9  934.97   130.8  924.37   145.4  918.16   156.3   915.3   167.9  910.51
   178.7   901.8   181.7  900.28   184.7   899.2     196  898.75   212.9  898.81
   220.2  900.25   224.3  902.14   235.3  911.01   241.1  913.04   266.6  915.93
   292.6  923.62   317.5  927.59   326.8  927.32   332.5  928.27   358.9  938.01
   372.3   945.4     391     954   399.5  956.56   412.2  957.15   423.6  963.31
#Mann= 3 ,-1,0
       0      .1       0   181.7    .045       0   220.2      .1       0
Bank Sta=181.7,220.2
XS Rating Curve= 0 ,0
Exp/Cntr(USF)=0,0
Exp/Cntr=0.3,0.1

Type RM Length L Ch R = 1 ,2476    ,538.7,518.4,506.5
XS GIS Cut Line= 4
1669379.00928167439826.5754645561669404.71526385439929.399393284
1669538.06504642440114.1611402161669573.41077192440184.852591217
#Sta/Elev= 30
       0  962.26    22.6   958.2    51.5   946.6      68  934.83    76.2  932.74
    88.6  931.89     106  925.86   113.5  922.28   125.5  919.43   132.3  916.03
   139.3   910.5   145.1  908.14   159.6  905.26     188  901.74   203.6  901.21
   225.3  902.62   239.6  897.77   253.9  897.18   272.6  896.78  278.17897.1849
   285.4  899.59   291.2  903.51   297.3  909.26   307.2  921.75     322  937.22
   345.4  956.63   354.4  960.74   385.7  970.64   405.7  982.92   412.9   985.1
#Mann= 4 ,-1,0
       0     .06       0      50      .1       0   253.9    .045       0
  278.17      .1       0
Bank Sta=253.9,278.17
XS Rating Curve= 0 ,0
Exp/Cntr(USF)=0,0
Exp/Cntr=0.3,0.1

Type RM Length L Ch R = 1 ,1958    ,498.1,480.6,467.7
XS GIS Cut Line= 3
1668995.96894224440424.5646370671669314.80345249440286.619910183
1669425.41950707440215.044816045
#Sta/Elev= 30
       0 1003.03     8.9  999.49    17.6  994.32    30.6  982.45    39.4  972.69
    43.7  970.12    56.8  965.74    74.2   963.3    78.6  961.63    97.5  942.71
   106.6  930.26   113.5  922.84   117.8  920.81   135.3  920.06   148.3  918.37
   151.2  917.33   174.5  899.12   182.7  893.95   191.8  892.91   200.6  892.92
     207   893.9   219.2  897.96   225.2  899.02     280  902.67   318.3   908.4
   331.4  916.16   355.6  922.69   407.7  934.93   459.8  944.75   479.1  949.08
#Mann= 3 ,-1,0
       0      .1       0   182.7    .045       0     207      .1       0
Bank Sta=182.7,207
XS Rating Curve= 0 ,0
Exp/Cntr(USF)=0,0
Exp/Cntr=0.3,0.1

Type RM Length L Ch R = 1 ,1477    ,470.2,480.5,489.6
XS GIS Cut Line= 4
1669515.93669682440823.1430313481669552.08573427440720.479765009
1669570.88323374440467.4365029061669620.04592466440389.354582028
#Sta/Elev= 30
       0 1001.33      24  991.64    53.7  977.63    83.3  967.58   116.3   953.3
   120.8  949.87   128.8  941.63   152.9  921.28   157.4  916.56   168.9  902.05
     173  900.26     189  900.17     193  898.42     201  891.97   204.1  890.65
   209.1  889.92   221.1  889.81   237.1  890.59   249.2  893.62   253.2  894.02
   265.2  894.27   273.2  895.68   309.3  896.93   317.4  898.26   325.4  900.93
   341.4  907.72   403.8   928.9     418  932.69   446.4  937.47   454.9  939.74
#Mann= 5 ,-1,0
       0      .1       0      70     .06       0  168.84      .1       0
   204.1    .045       0   237.1      .1       0
Bank Sta=204.1,237.1
XS Rating Curve= 0 ,0
Exp/Cntr(USF)=0,0
Exp/Cntr=0.3,0.1

Type RM Length L Ch R = 1 ,997     ,469.6,474.8,478.2
XS GIS Cut Line= 4
1669812.40421786440884.3455094551669865.10951445440832.811441675
 1670065.3896415440611.449195987 1670118.0949381440548.202840076
#Sta/Elev= 30
       0  969.08    16.9  962.74    34.1  952.35    55.5  937.21    70.4  928.44
    84.2  917.21    95.7  901.38    98.7  900.13     127  899.03   138.8  893.92
   203.5  892.28   214.8  888.38   231.8  889.04   251.1  886.78   268.3  886.38
   279.9  886.81   289.9  889.47   299.8  896.65   304.7  901.96   311.4  912.46
   322.6  925.23   330.9  932.48   340.5  943.04   349.2  951.12   364.4  962.24
   370.3     965   381.2  967.98   396.1  970.76   420.2  982.54   454.6  996.01
#Mann= 5 ,-1,0
       0      .1       0      40     .06       0  173.71      .1       0
   251.1    .045       0   279.9      .1       0
Bank Sta=251.1,279.9
XS Rating Curve= 0 ,0
Exp/Cntr(USF)=0,0
Exp/Cntr=0.3,0.1

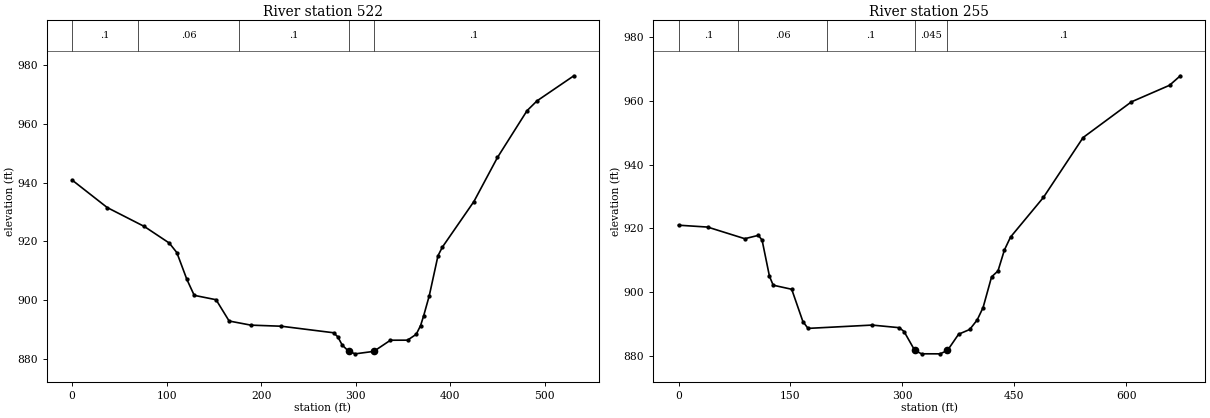
Type RM Length L Ch R = 1 ,522     ,270.8,267,263.7
XS GIS Cut Line= 4
1669955.49137094441172.6886586911670026.18282194441201.607888645
1670319.23138643441034.7306791191670410.47175529440961.341686779
#Sta/Elev= 30
       0  940.88    37.2  931.52    76.4  925.09   102.8  919.45   110.8  916.21
   121.4   907.1   129.2  901.67   152.3  900.18   166.1  892.94   189.1  891.54
   221.3  891.17   276.5  888.95     281  887.59   285.7  884.76   292.7   882.6
   299.5  881.78   319.1  882.62   336.7  886.41   354.8  886.43     364  888.43
   368.6   891.4   371.9  894.78   377.8  901.57     387  915.14   391.6  918.05
     425  933.58   449.9  948.55   481.2  964.47   491.7  967.79   530.7  976.33
#Mann= 5 ,-1,0
       0      .1       0      70     .06       0  176.38      .1       0
   292.7    .045       0   319.1      .1       0
Bank Sta=292.7,319.1
XS Rating Curve= 0 ,0
Exp/Cntr(USF)=0,0
Exp/Cntr=0.3,0.1

Type RM Length L Ch R = 1 ,255     ,,,
XS GIS Cut Line= 4
1670044.62873041441443.7941149041670125.43743068441480.525342302
1670424.18474685441260.137977916 1670478.0572137441054.443104489
#Sta/Elev= 30
       0  920.95      39  920.36    88.8  916.71     107  917.76     112  916.26
   121.9  904.89   126.9  902.11   151.7  900.83   166.7  890.69   173.6  888.55
   259.4  889.59   295.9  888.77   302.3  887.56   316.6  881.65   325.7  880.57
   350.6  880.56   360.5  881.63   375.4  886.72   390.3  888.21   400.3   891.2
   408.2  895.08   419.6  904.73   428.2  906.59   436.8  913.16     445  917.22
   489.1  929.67   542.3  948.47   607.1  959.68   658.1  964.87   672.6  967.86
#Mann= 5 ,-1,0
       0      .1       0      80     .06       0  198.77      .1       0
   316.6    .045       0   360.5      .1       0
Bank Sta=316.6,360.5
XS Rating Curve= 0 ,0
Exp/Cntr(USF)=0,0
Exp/Cntr=0.3,0.1
LCMann Table=0

Chan Stop Cuts=-1
Use User Specified Reach Order=0
Composite Channel Slope=5